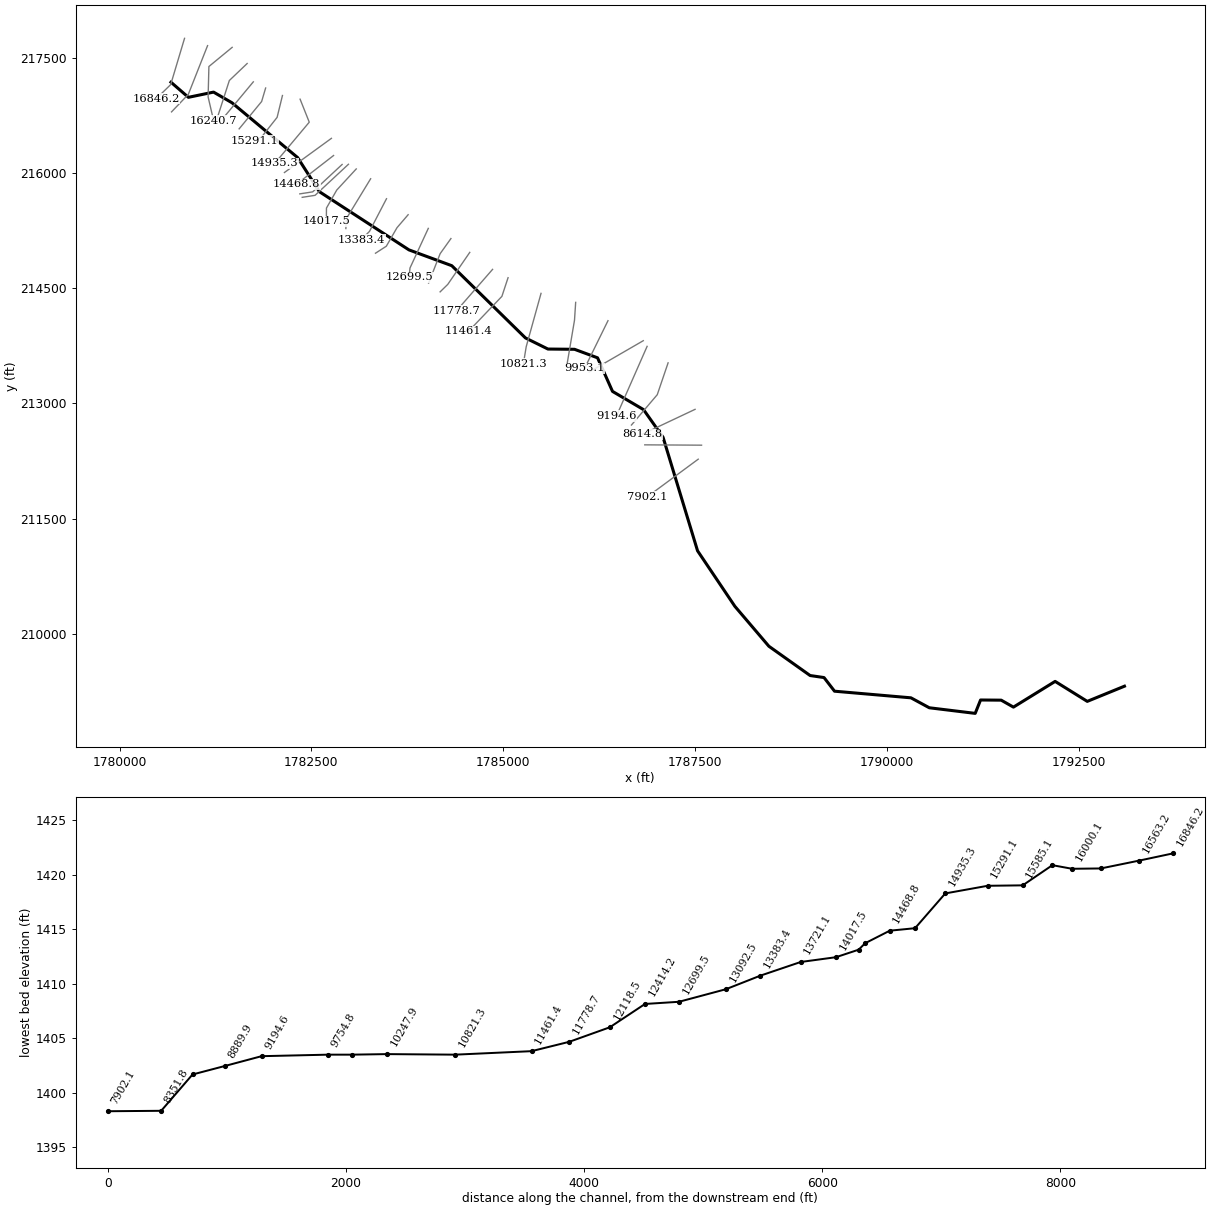
--- BIGRN.prj (project) ---

Proj Title=BIGRN
Current Plan=p01
Default Exp/Contr=0,0
English Units
Geom File=g01
Flow File=f01
Plan File=p01
BEGIN DESCRIPTION:
END DESCRIPTION:
DSS Export Rating Curves= 0
DSS Export Rating Curve Sorted= 0
DSS Export Volume Flow Curves= 0
DXF OffsetX= 0
DXF OffsetY= 0
DXF ScaleX= 0
DXF ScaleY= 0

--- BIGRN.p01 (plan) ---

Plan Title=Floodplain
Program Version=4.00
Geom File=g01
Flow File=f01
K Sum by GR=0
Std Step Tol=0.01
Critical Tol=0.01
Num of Std Step Trials=20
Max Error Tol=0.3
Flow Tol Ratio=0.001
Split Flow NTrial=30
Split Flow Tol=0.02
Split Flow Ratio=0.02
Log Output Level=0
Friction Slope Method=1
Unsteady Friction Slope Method=2
Unsteady Bridges Friction Slope Method=1
Global Log Level=0
CheckData=False
Run HTab=0
Run UNet=0
Run PostProcess=0
UNET Theta=0
UNET Theta Warmup=0
UNET ZTol=0
UNET ZSATol=0
UNET MxIter=0
UNET MaxInSteps=0
UNET DtIC=0
UNET DtMin=0
UNET MaxCRTS=0
UNET WFStab=0
UNET SFStab=0
UNET WFX=0
UNET SFX=0
UNET DSS MLevel=0
UNET DZMax Abort=0
UNET Convert EG Bridges=0
UNET Use Existing IB Tables=0
UNET Froude Limit=0
UNET Froude Power=0
Write IC File=0
Echo Input=False
Echo Output=False
Write Detailed=0

--- BIGRN.f01 (steady flow) ---

Flow Title=NFF Regression Equation
Program Version=4.10
Number of Profiles= 1
Profile Names=P100yr
River Rch & RM=BIGRN,Main            ,16846.2
476.9965
River Rch & RM=BIGRN,Main            ,16563.2
477.4397
River Rch & RM=BIGRN,Main            ,16000.1
555.8239
River Rch & RM=BIGRN,Main            ,14681.3
567.0902
River Rch & RM=BIGRN,Main            ,14262.2
656.4138
River Rch & RM=BIGRN,Main            ,13721.1
 719.531
River Rch & RM=BIGRN,Main            ,11778.7
788.4101
River Rch & RM=BIGRN,Main            ,10821.3
829.2311
River Rch & RM=BIGRN,Main            ,7502
 882.012
River Rch & RM=BIGRN,Main            ,7165.3
1168.158
River Rch & RM=BIGRN,Main            ,529.2
1297.393
River Rch & RM=BIGRN,Main            ,169.6
1298.314
Boundary for River Rch & Prof#=BIGRN,Main            , 1
Up Type= 0
Dn Type= 3
Dn Slope=0.0086
DSS Import GetInterval= 0
DSS Import GetPeak= 0
DSS Import FillOption= 0

--- BIGRN.g01 (geometry) ---

Geom Title=USGS 10m DEM
Program Version=4.10

River Reach=BIGRN           ,Main
Reach XY= 30
     1780669.692       217182.95     1780897.033      216986.085
     1781224.873      217054.075     1781464.664      216915.373
     1782320.384      216201.403     1782604.704      215756.701
     1783770.937      214999.408     1784329.277      214793.342
     1785289.123      213852.756     1785582.272      213707.921
     1785928.849      213704.626     1786228.932       213593.66
     1786423.829      213156.396     1786828.325      212918.842
     1787082.761       212558.64     1787532.147      211080.404
     1788018.309      210357.511     1788461.572      209837.404
     1788999.126      209456.056     1789180.208      209429.695
     1789317.246      209252.015      1790312.92      209165.775
     1790551.924      209036.213     1791150.357      208963.226
     1791220.169      209137.483     1791489.068      209135.283
     1791648.772      209044.701     1792191.926      209379.716
     1792610.737      209119.461     1793095.418      209317.226

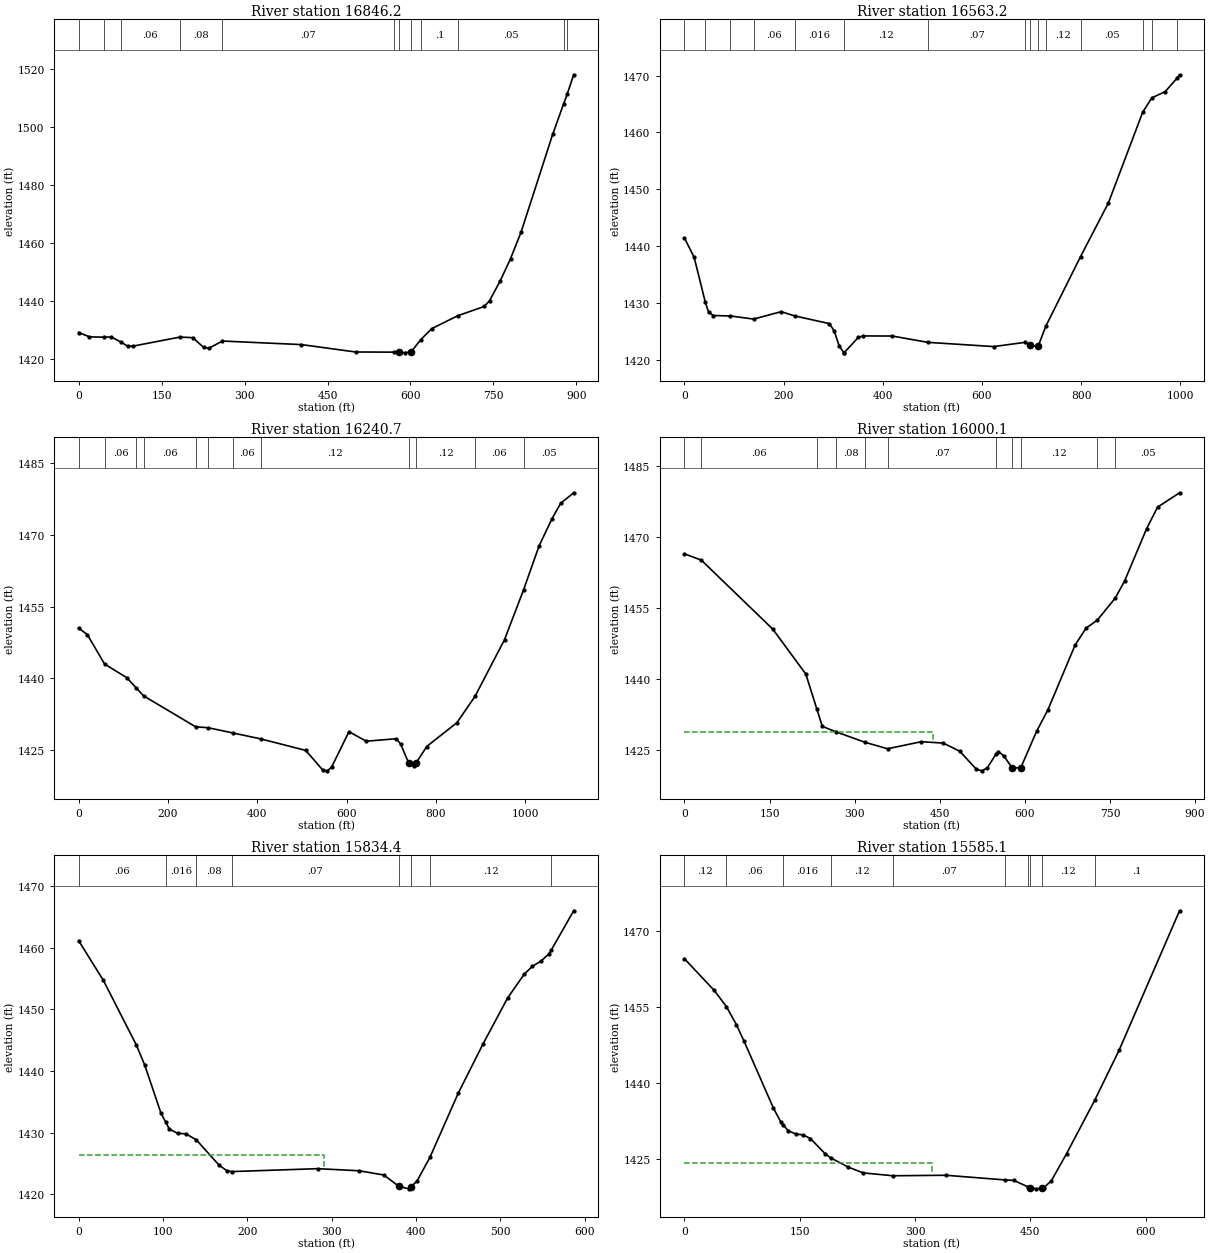
Type RM Length L Ch R = 1 ,16846.2 ,293.1,283,272.6
XS GIS Cut Line= 3
     1780846.605      217754.304     1780666.251       217151.87
     1780475.447      216966.237
#Sta/Elev= 30
       0    1429    19.6 1427.49   45.161427.392      59 1427.48   75.841425.761
    88.4 1424.32    98.3 1424.29   183.21427.416   206.3 1427.22     226 1423.86
   235.8 1423.58  259.951426.053   402.9 1424.82   501.1 1422.26  570.851422.213
   579.7 1422.24   589.6 1421.97  601.43 1422.39  618.721426.551   638.4 1430.33
  685.561434.808   733.4    1438   742.9 1439.96     762 1446.76     781 1454.56
     800 1463.72     857 1497.45   876.91508.051  883.281511.387   895.1 1518.09
#Mann= 12 ,-1 , 0
       0     .12       0   45.16    .016       0   75.84     .06       0
   183.2     .08       0  259.95     .07       0  570.85     .12       0
   579.7    .045       0  601.43     .12       0  618.72      .1       0
  685.56     .05       0   876.9     .12       0  883.28     .06       0
Bank Sta=579.7,601.43
XS Rating Curve= 0 ,0
Exp/Cntr=0.3,0.1

Type RM Length L Ch R = 1 ,16563.2 ,304.3,322.5,339.5
XS GIS Cut Line= 3
     1781146.766      217659.279     1780895.898      217024.731
     1780677.148      216796.432
#Sta/Elev= 30
       0 1441.46    19.5  1438.1   42.041430.205    48.7 1428.42    58.5 1427.86
   92.811427.784  139.611427.234     195 1428.54  221.99  1427.8   292.4 1426.44
   302.2 1425.12   311.9 1422.55   321.7 1421.31     3221421.329   350.9 1424.04
   360.7 1424.28   419.2 1424.26  491.111423.151   623.8 1422.41  686.871423.152
  697.031422.618  713.311422.478  729.26 1426.07  798.94 1438.22   854.8 1447.58
  924.111463.541  942.47 1466.07   969.8 1467.19  994.061469.607   998.5 1470.13
#Mann= 15 ,-1 , 0
       0     .12       0   42.04    .016       0   92.81     .08       0
  139.61     .06       0  221.99    .016       0     322     .12       0
  491.11     .07       0  686.87     .06       0  697.03    .045       0
  713.31     .06       0  729.26     .12       0  798.94     .05       0
  924.11      .1       0  942.47     .05       0  994.06      .1       0
Bank Sta=697.03,713.31
XS Rating Curve= 0 ,0
Exp/Cntr=0.3,0.1

Type RM Length L Ch R = 1 ,16240.7 ,247.3,240.6,233.6
XS GIS Cut Line= 4
       1781467.2       217636.81     1781164.115      217387.281
     1781153.856      216990.884     1781226.315      216679.779
#Sta/Elev= 30
       0 1450.51    19.6 1449.13   58.091442.978     108  1440.1  129.531437.907
  145.511436.305  261.891429.825  290.311429.618  345.631428.524  407.451427.293
   508.6 1424.87   547.3 1420.69     557 1420.59   566.7 1421.41   605.4  1428.8
     644  1426.8   711.8 1427.32   721.4 1426.14  739.531422.134   750.4 1421.54
  755.231422.159   779.4 1425.69   847.2 1430.69  887.731436.217   953.7 1448.08
  996.221458.486  1031.1 1467.73  1060.2 1473.46  1079.5 1476.66  1108.6 1478.86
#Mann= 12 ,-1 , 0
       0     .12       0   58.09     .06       0  129.53    .016       0
  145.51     .06       0  261.89    .016       0  290.31     .08       0
  345.63     .06       0  407.45     .12       0  739.53    .045       0
  755.23     .12       0  887.73     .06       0  996.22     .05       0
Bank Sta=739.53,755.23
XS Rating Curve= 0 ,0
Exp/Cntr=0.3,0.1

Type RM Length L Ch R = 1 ,16000.1 ,173.9,165.7,156.6
XS GIS Cut Line= 3
     1781662.513      217426.307     1781430.308      217204.952
     1781261.037      216679.779
#Sta/Elev= 30
       0  1466.5   29.811465.153   155.5 1450.58   213.9 1441.05  233.131433.724
     243 1429.97   267.21428.812  318.721426.585  357.961425.233   417.6 1426.73
   456.3 1426.43   485.4 1424.69   514.4 1420.91   524.1 1420.56   533.8  1421.2
  549.241424.137   553.1 1424.65   562.8 1423.75  577.721421.158  592.791421.215
   620.9 1428.99   640.3  1433.4   688.7 1447.23     708 1450.78  727.481452.438
   759.3 1457.13   775.8 1460.75   814.5 1471.81   833.9 1476.38   872.6 1479.42
#Mann= 11 ,-1 , 0
       0     .12       0   29.81     .06       0  233.13    .016       0
   267.2     .08       0  318.72     .06       0  357.96     .07       0
  549.24     .12       0  577.72    .045       0  592.79     .12       0
  727.48     .06       0   759.3     .05       0
#XS Ineff= 2 , 0
          437.56 1428.72
Permanent Ineff=
       F       F
Bank Sta=577.72,592.79
XS Rating Curve= 0 ,0
Exp/Cntr=0.3,0.1

Type RM Length L Ch R = 1 ,15834.4 ,249.2,249.3,249.4
XS GIS Cut Line= 2
     1781742.808      217187.591     1781367.374      216736.202
#Sta/Elev= 30
       0 1461.13    29.4 1454.68    68.5  1444.2    78.3 1440.99    97.8 1433.11
  103.231431.714   107.6 1430.59   117.4 1429.88   127.2 1429.81  139.621428.831
   166.4 1424.75   176.1  1423.8  181.591423.688   283.8 1424.16   332.7 1423.82
     362 1423.13  379.611421.316   391.4 1420.89  393.661421.175   401.2 1422.12
  416.911426.082   450.1 1436.37   479.5 1444.36   508.8 1451.85   528.4 1455.68
   538.2 1456.98     548 1457.78   557.8    1459  560.591459.621   587.1 1465.97
#Mann= 8 ,-1 , 0
       0     .06       0  103.23    .016       0  139.62     .08       0
  181.59     .07       0  379.61    .045       0  393.66     .07       0
  416.91     .12       0  560.59      .1       0
#XS Ineff= 2 , 0
          291.02 1426.42
Permanent Ineff=
       F       F
Bank Sta=379.61,393.66
XS Rating Curve= 0 ,0
Exp/Cntr=0.3,0.1

Type RM Length L Ch R = 1 ,15585.1 ,293.5,294,294.5
XS GIS Cut Line= 3
     1781903.398      217107.296     1781851.315      216931.515
     1781558.346      216575.612
#Sta/Elev= 30
       0 1464.45    38.6 1458.22   54.541455.026    67.5 1451.47    77.2 1448.31
   115.8 1434.97   125.4 1432.23  128.511431.675   135.1  1430.5   144.7 1429.88
   154.4 1429.68     164 1428.96   183.3 1425.94  190.371425.146   212.8 1423.36
   232.4 1422.19  271.281421.621   340.3 1421.72  416.751420.804   428.5 1420.71
  447.291419.418     450 1419.28     458 1419.04     465  1419.2   467.8 1419.27
   477.6 1420.67   497.2 1425.96  533.921436.522   565.8 1446.45   644.3 1473.92
#Mann= 10 ,-1 , 0
       0     .12       0   54.54     .06       0  128.51    .016       0
  190.37     .12       0  271.28     .07       0  416.75     .06       0
  447.29     .12       0     450    .045       0     465     .12       0
  533.92      .1       0
#XS Ineff= 2 , 0
          322.19 1424.19
Permanent Ineff=
       F       F
Bank Sta=450,465
XS Rating Curve= 0 ,0
Exp/Cntr=0.3,0.1

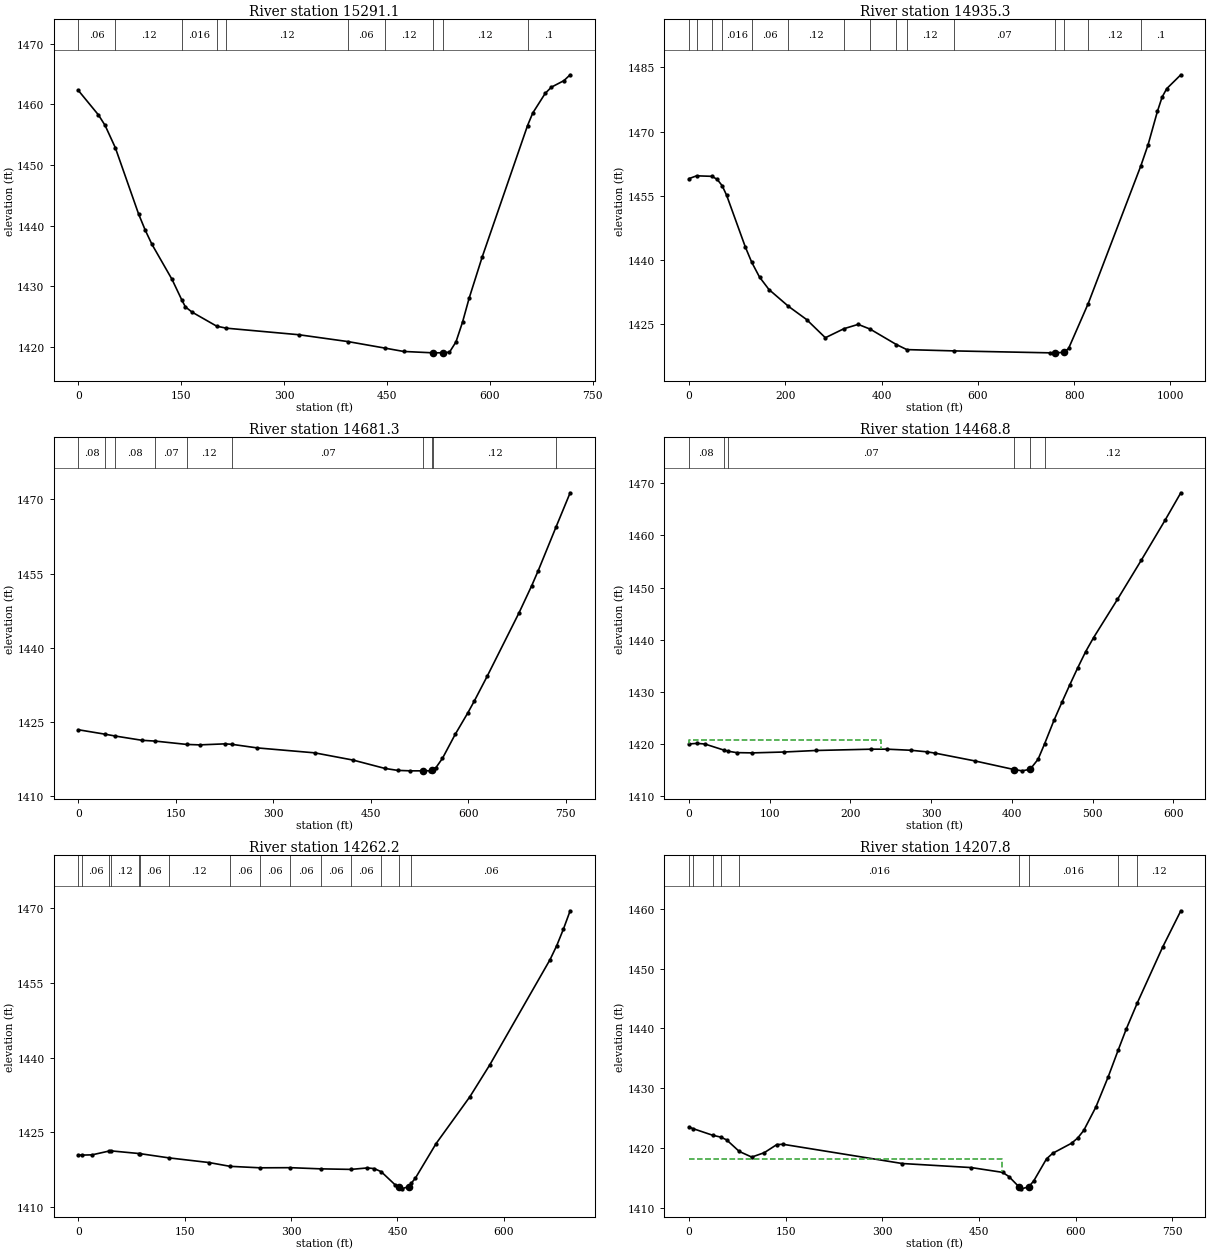
Type RM Length L Ch R = 1 ,15291.1 ,356.4,355.8,355
XS GIS Cut Line= 4
     1782122.582       217009.64     1782053.138      216725.352
     1781857.825      216477.956     1781764.509      216421.532
#Sta/Elev= 30
       0 1462.31    29.3 1458.27      39 1456.54   53.911452.862    87.8 1441.93
    97.6 1439.23   107.3 1436.91   136.6 1431.12  150.851427.721   156.1 1426.58
   165.8 1425.72   201.71423.401  215.561423.073   321.3 1421.99  393.091420.857
  446.611419.788   474.1 1419.23  517.11    1419   531.4 1419.01     541  1419.1
   550.5 1420.81   560.1 1424.09   569.6 1427.99   588.7 1434.82  654.821456.514
   662.4 1458.58   680.6 1461.83   689.6 1462.85   707.8 1463.92   716.9 1464.89
#Mann= 10 ,-1 , 0
       0     .06       0   53.91     .12       0  150.85    .016       0
   201.7     .08       0  215.56     .12       0  393.09     .06       0
  446.61     .12       0  517.11    .045       0   531.4     .12       0
  654.82      .1       0
Bank Sta=517.11,531.4
XS Rating Curve= 0 ,0
Exp/Cntr=0.3,0.1

Type RM Length L Ch R = 1 ,14935.3 ,251.8,253.9,249
XS GIS Cut Line= 3
     1782352.617      216961.897     1782471.974      216662.418
     1782022.756      216126.393
#Sta/Elev= 30
       0 1459.02   15.811459.673   47.821459.555    58.6 1458.83   68.761457.393
    78.2 1455.12   117.2 1442.99  130.281439.477   146.5 1436.01   166.1  1433.1
   206.71429.166   244.2 1426.09   283.3 1421.83  322.011423.948   351.5 1424.95
  376.481423.838  430.821420.241  452.511419.057  549.551418.756   749.8  1418.3
   759.5 1418.31   778.9  1418.4   788.6 1419.32  829.371429.816  938.861462.047
   953.8 1466.95   973.2 1474.75   982.9 1478.07   992.6 1480.06  1021.8 1483.29
#Mann= 15 ,-1 , 0
       0    .016       0   15.81     .12       0   47.82     .06       0
   68.76    .016       0  130.28     .06       0   206.7     .12       0
  322.01    .016       0  376.48     .12       0  430.82     .08       0
  452.51     .12       0  549.55     .07       0   759.5    .045       0
   778.9     .07       0  829.37     .12       0  938.86      .1       0
Bank Sta=759.5,778.9
XS Rating Curve= 0 ,0
Exp/Cntr=0.3,0.1

Type RM Length L Ch R = 1 ,14681.3 ,218.2,212.6,212.6
XS GIS Cut Line= 2
     1782760.603      216451.914     1782148.624      216007.036
#Sta/Elev= 30
       0 1423.42   41.681422.509   57.041422.144    98.3 1421.28  118.281421.126
  166.811420.452   186.7 1420.36     226 1420.57  236.471420.469   275.1 1419.75
   363.6 1418.75   422.5 1417.29   471.6  1415.6   491.3  1415.2     511 1415.11
   530.6 1415.11   540.4 1415.13  544.191415.377  545.781415.481   550.2 1415.77
   560.1 1417.62   579.7 1422.47   599.4 1426.88   609.2 1429.24   628.9 1434.22
     678 1447.08   697.6 1452.59   707.5  1455.6   734.61464.336   756.6 1471.35
#Mann= 10 ,-1 , 0
       0     .08       0   41.68     .06       0   57.04     .08       0
  118.28     .07       0  166.81     .12       0  236.47     .07       0
   530.6    .045       0  544.19     .07       0  545.78     .12       0
   734.6      .1       0
Bank Sta=530.6,544.19
XS Rating Curve= 0 ,0
Exp/Cntr=0.3,0.1

Type RM Length L Ch R = 1 ,14468.8 ,204.6,206.6,208.6
XS GIS Cut Line= 2
     1782788.815       216228.39     1782307.044      215855.126
#Sta/Elev= 30
       0 1420.03     9.8 1420.14    19.7 1420.02    42.91418.871   48.461418.641
      59 1418.37    78.6 1418.32     118 1418.49   157.3 1418.78   226.1 1419.03
   245.8 1419.03   275.2 1418.82   294.9 1418.52   304.7 1418.28   353.9 1416.79
     403 1415.12   412.8 1414.88   422.7 1415.18   432.5 1417.09  440.611420.061
   452.2 1424.55     462    1428   471.8 1431.36   481.7 1434.64   491.5 1437.73
   501.3 1440.41   530.8 1447.72   560.3 1455.22   589.8 1462.89   609.4 1468.17
#Mann= 6 ,-1 , 0
       0     .08       0    42.9     .12       0   48.46     .07       0
     403    .045       0   422.7     .07       0  440.61     .12       0
#XS Ineff= 2 , 0
          238.39 1420.84
Permanent Ineff=
       F       F
Bank Sta=403,422.7
XS Rating Curve= 0 ,0
Exp/Cntr=0.3,0.1

Type RM Length L Ch R = 1 ,14262.2 ,54.3,54.3,54.4
XS GIS Cut Line= 3
     1782900.143      216111.636     1782516.462      215754.866
     1782348.927      215728.824
#Sta/Elev= 30
       0 1420.51    4.691420.476    19.4 1420.53   43.421421.291   45.66 1421.33
   86.051420.787   86.631420.775   127.61419.927   184.3 1418.99  213.911418.231
  256.531417.936  299.151417.963  341.771417.729  384.391417.619   407.5 1417.91
   417.2 1417.78  427.011417.167   446.3 1414.59  451.651414.116     456 1413.73
   465.7 1414.18  469.631414.877   475.4  1415.9   504.5 1422.79   552.2 1432.17
   580.4 1438.58   665.2 1459.59   674.6 1462.38     684 1465.68   693.5 1469.35
#Mann= 15 ,-1 , 0
       0    .016       0    4.69     .06       0   43.42    .016       0
   45.66     .12       0   86.05    .016       0   86.63     .06       0
   127.6     .12       0  213.91     .06       0  256.53     .06       0
  299.15     .06       0  341.77     .06       0  384.39     .06       0
  427.01     .06       0  451.65    .045       0  469.63     .06       0
Bank Sta=451.65,465.7
XS Rating Curve= 0 ,0
Exp/Cntr=0.3,0.1

Type RM Length L Ch R = 1 ,14207.8 ,183.4,190.3,197.1
XS GIS Cut Line= 3
     1782982.608      216114.241     1782547.712      215709.727
     1782380.177      215683.685
#Sta/Elev= 30
       0 1423.48    6.531423.211   37.061422.102   49.151421.807    58.4 1421.34
   78.041419.401    97.4 1418.46   116.8 1419.19   136.3 1420.55     146  1420.6
     331 1417.38   438.2  1416.7   486.8  1415.9   496.6  1415.2   512.6 1413.44
     516 1413.14   527.6 1413.48   535.5 1414.53     555 1418.16   564.7  1419.1
   593.9 1420.78   603.4 1421.65   612.8 1422.92   631.6 1426.83   650.5 1431.82
  666.171436.344   678.7 1439.88  696.151444.324   735.2  1453.6   763.5  1459.7
#Mann= 9 ,-1 , 0
       0    .016       0    6.53     .06       0   37.06    .016       0
   49.15     .08       0   78.04    .016       0   512.6    .045       0
   527.6    .016       0  666.17     .06       0  696.15     .12       0
#XS Ineff= 2 , 0
          485.45 1418.11
Permanent Ineff=
       F       F
Bank Sta=512.6,527.6
XS Rating Curve= 0 ,0
Exp/Cntr=0.3,0.1

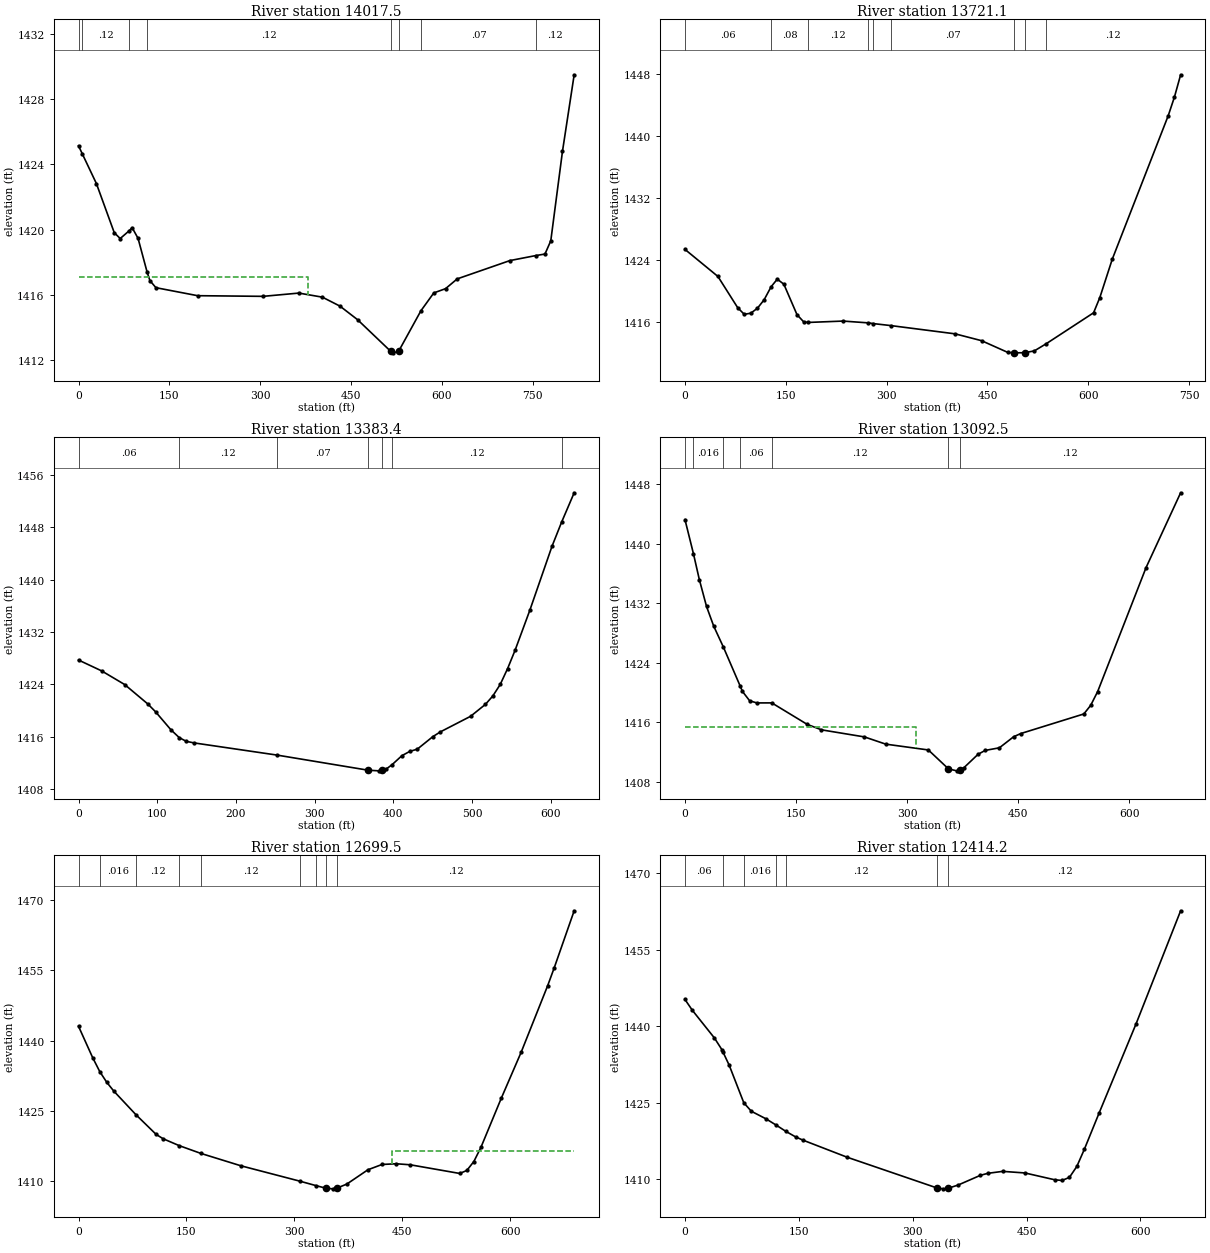
Type RM Length L Ch R = 1 ,14017.5 ,297.1,296.5,295.8
XS GIS Cut Line= 4
     1783084.171      216053.477     1782830.698      215779.171
      1782696.15      215543.928     1782694.414      215370.317
#Sta/Elev= 30
       0 1425.13    6.081424.652    29.5 1422.82      59 1419.81    68.8 1419.45
   83.941419.936    88.5 1420.12    98.3 1419.46     1131417.425   117.9 1416.87
   127.8 1416.44   196.6 1415.95   304.7 1415.91   363.7 1416.11   402.5 1415.86
   431.6 1415.31   460.6 1414.48   515.1 1412.55   518.7 1412.45   528.3 1412.54
  565.131415.024   586.4 1416.12   605.8 1416.38   625.1 1416.98     712  1418.1
  755.11 1418.41   769.9  1418.5   779.5 1419.31   798.8 1424.79   818.1 1429.48
#Mann= 8 ,-1 , 0
       0     .08       0    6.08     .12       0   83.94     .08       0
     113     .12       0   515.1    .045       0   528.3     .12       0
  565.13     .07       0  755.11     .12       0
#XS Ineff= 2 , 0
          378.74 1417.11
Permanent Ineff=
       F       F
Bank Sta=515.1,528.3
XS Rating Curve= 0 ,0
Exp/Cntr=0.3,0.1

Type RM Length L Ch R = 1 ,13721.1 ,336,337.7,339.1
XS GIS Cut Line= 3
     1783271.864      215925.605     1782955.527      215406.487
     1782948.948      215277.168
#Sta/Elev= 30
       0 1425.36      49 1421.87    78.4 1417.84    88.2 1416.98      98 1417.13
   107.8 1417.77   117.7 1418.85  128.171420.542   137.3 1421.52   147.1 1420.87
   166.7 1416.93   176.5 1416.02  182.641415.932   235.3 1416.11  272.891415.876
  280.241415.784  305.841415.532     402 1414.46   441.2 1413.58   480.4 1412.06
   490.2 1412.01  505.211412.025   519.7 1412.26  537.051413.165   607.9 1417.18
   617.2 1419.15   635.7  1424.1   718.9 1442.61   728.2 1445.03   737.4  1447.9
#Mann= 9 ,-1 , 0
       0     .06       0  128.17     .08       0  182.64     .12       0
  272.89     .07       0  280.24     .06       0  305.84     .07       0
   490.2    .045       0  505.21     .07       0  537.05     .12       0
Bank Sta=490.2,505.21
XS Rating Curve= 0 ,0
Exp/Cntr=0.3,0.1

Type RM Length L Ch R = 1 ,13383.4 ,292,290.9,290
XS GIS Cut Line= 3
     1783478.462      215665.623     1783257.107      215240.275
     1783150.771      215133.938
#Sta/Elev= 30
       0  1427.7    29.4 1426.04    58.7 1423.95    88.1 1420.98    97.9 1419.79
   117.4 1417.04     1281415.839     137 1415.27   146.8 1415.03  252.041413.173
  368.091410.856   381.6 1410.76  385.181410.873   391.4 1411.07  398.371411.689
     411 1413.08   420.8 1413.72   430.6 1414.08   450.1 1415.97   459.9 1416.72
   498.3  1419.1   517.1 1420.92   526.5  1422.2   535.9 1423.96   545.3 1426.39
   554.7 1429.16   573.5 1435.29   601.7 1445.08  613.871448.762   629.9 1453.27
#Mann= 7 ,-1 , 0
       0     .06       0     128     .12       0  252.04     .07       0
  368.09    .045       0  385.18     .07       0  398.37     .12       0
  613.87    .016       0
Bank Sta=368.09,385.18
XS Rating Curve= 0 ,0
Exp/Cntr=0.3,0.1

Type RM Length L Ch R = 1 ,13092.5 ,390.8,393.1,394.9
XS GIS Cut Line= 4
      1783760.58      215457.289      1783615.18      215288.018
     1783476.291      215047.133     1783335.232      214955.987
#Sta/Elev= 30
       0 1443.21   11.371438.662    19.4 1435.16    29.1 1431.56    38.8 1428.92
    51.9  1426.1   74.381420.917    77.6 1420.16    87.3 1418.91      97 1418.62
   117.21418.625   164.9 1415.75   184.3 1415.01   242.3 1414.06   271.1 1413.09
   328.6 1412.31  355.78 1409.77     367 1409.51   370.81409.674   376.6 1409.93
   395.7 1411.73   405.3 1412.25   424.5  1412.6   443.7 1414.08   453.3 1414.51
   538.5 1417.14   547.8  1418.3   557.2 1420.15   622.5 1436.77   669.2 1446.81
#Mann= 7 ,-1 , 0
       0     .12       0   11.37    .016       0    51.9     .08       0
   74.38     .06       0   117.2     .12       0  355.78    .045       0
   370.8     .12       0
#XS Ineff= 2 , 0
          312.07 1415.41
Permanent Ineff=
       F       F
Bank Sta=355.78,370.8
XS Rating Curve= 0 ,0
Exp/Cntr=0.3,0.1

Type RM Length L Ch R = 1 ,12699.5 ,283.9,285.3,286.5
XS GIS Cut Line= 3
     1784023.166      215279.338     1783784.451      214762.845
       1783773.6      214643.487
#Sta/Elev= 30
       0 1443.04    19.6 1436.37   29.611433.351    39.2  1431.1      49 1429.22
   79.941424.152   107.9 1419.97   117.7 1419.04  140.04 1417.57  170.191415.911
   225.6 1413.28  307.791409.989  329.961409.049   343.4 1408.51   353.2 1408.36
  359.181408.519   372.8 1409.37   402.2 1412.43   421.8 1413.56   441.5 1413.71
   461.1 1413.49   529.8 1411.64   539.6 1412.28   549.4 1414.19   559.2  1417.2
   587.4 1427.65   615.1 1437.49     652 1451.71   661.2 1455.56   688.8 1467.68
#Mann= 9 ,-1 , 0
       0     .12       0   29.61    .016       0   79.94     .12       0
  140.04     .08       0  170.19     .12       0  307.79     .06       0
  329.96     .12       0   343.4    .045       0  359.18     .12       0
#XS Ineff= 2 , 0
                          436.33         1416.44
Permanent Ineff=
       F       F
Bank Sta=343.4,359.18
XS Rating Curve= 0 ,0
Exp/Cntr=0.3,0.1

Type RM Length L Ch R = 1 ,12414.2 ,300.7,295.7,290.4
XS GIS Cut Line= 3
     1784318.305      215146.959     1784177.246      214949.477
     1784027.507      214567.532
#Sta/Elev= 30
       0 1445.23     9.7 1443.12    38.8 1437.69    48.5 1435.44   50.031434.957
    58.2 1432.38   77.491425.008    87.4 1423.35   106.8 1421.86  119.831420.664
  132.851419.416   145.6 1418.34   155.3  1417.7   213.6 1414.35     332 1408.33
   340.4 1408.16     347 1408.29   359.9 1408.91   389.2 1410.81     399  1411.2
   418.5 1411.58   447.8 1411.27   486.9 1409.94   496.6  1409.8   506.4  1410.4
   516.2 1412.55     526 1415.88   545.5    1423   594.3  1440.5   652.9  1462.6
#Mann= 7 ,-1 , 0
       0     .06       0   50.03     .12       0   77.49    .016       0
  119.83     .08       0  132.85     .12       0     332    .045       0
     347     .12       0
Bank Sta=332,347
XS Rating Curve= 0 ,0
Exp/Cntr=0.3,0.1

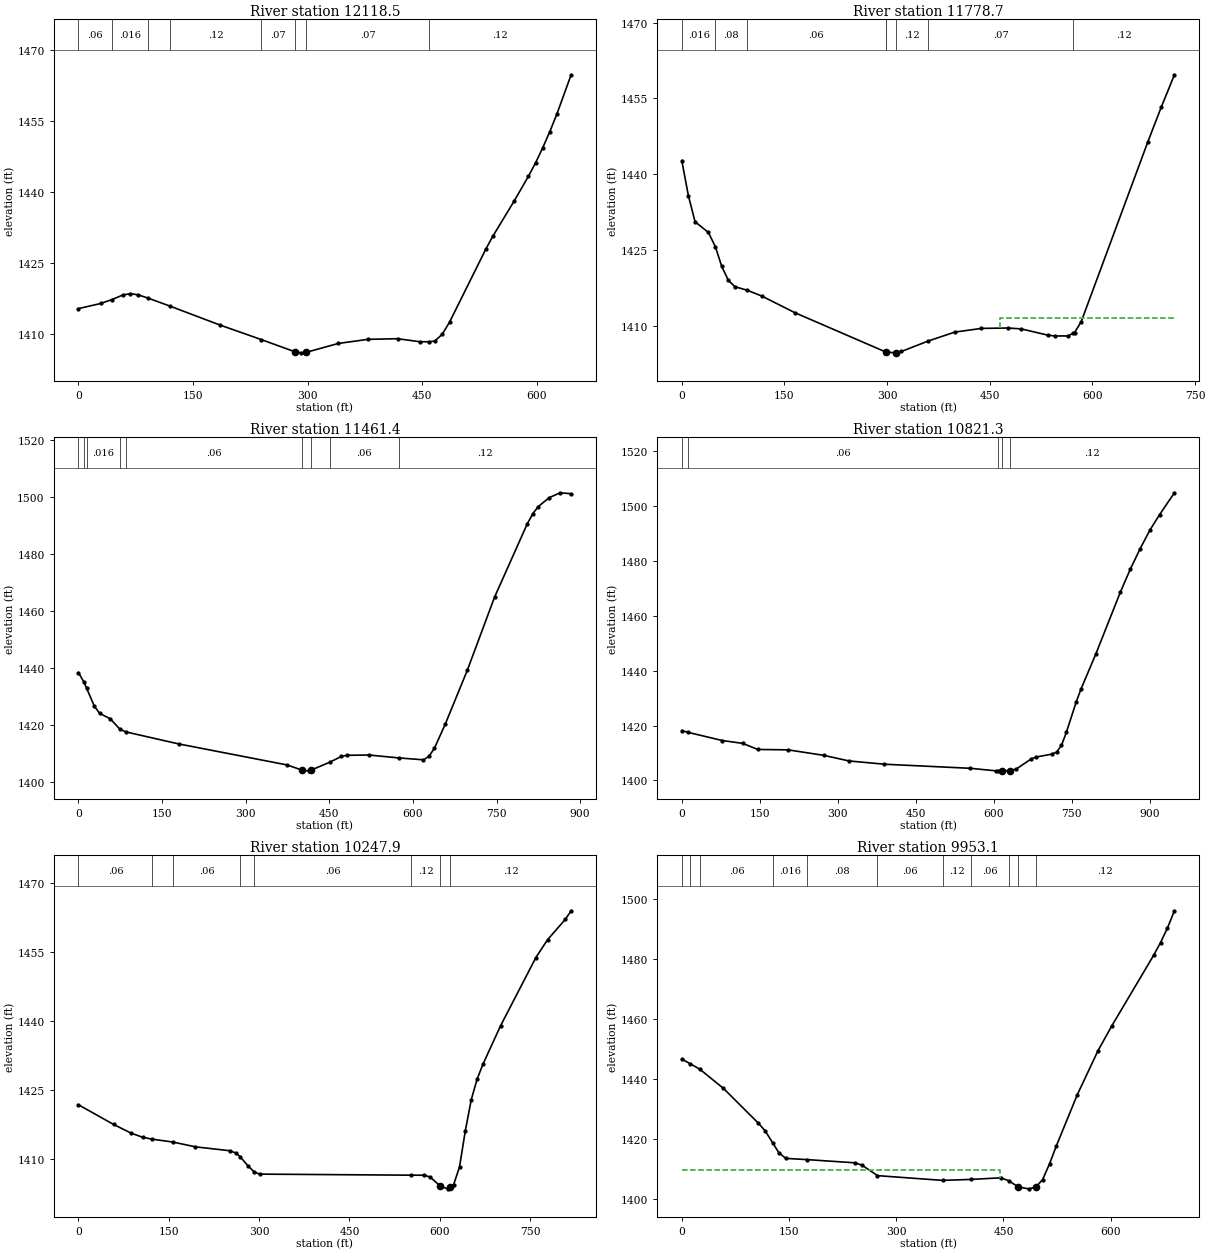
Type RM Length L Ch R = 1 ,12118.5 ,342.4,339.9,337.3
XS GIS Cut Line= 3
     1784563.531      214966.838     1784277.073      214550.171
     1784177.246      214452.515
#Sta/Elev= 30
       0 1415.36    29.2 1416.44   43.971417.274    58.3 1418.24    68.1 1418.51
    77.8 1418.27   90.461417.612  120.03 1415.87   184.8 1411.92  239.311408.825
   283.6 1406.24   291.7 1406.02   298.6 1406.14   340.3    1408   379.2 1408.87
   418.1    1409   447.3 1408.36  459.281408.362   466.7  1408.5   476.5 1409.95
   486.2 1412.55   533.6 1427.94   542.9 1430.68   570.8  1438.1   589.4  1443.3
   598.7 1446.13     608 1449.27   617.4 1452.72   626.7 1456.46   645.3 1464.71
#Mann= 8 ,-1 , 0
       0     .06       0   43.97    .016       0   90.46     .08       0
  120.03     .12       0  239.31     .07       0   283.6    .045       0
   298.6     .07       0  459.28     .12       0
Bank Sta=283.6,298.6
XS Rating Curve= 0 ,0
Exp/Cntr=0.3,0.1

Type RM Length L Ch R = 1 ,11778.7 ,318.3,317.2,316.2
XS GIS Cut Line= 2
      1784860.84      214745.484      1784387.75      214202.949
#Sta/Elev= 30
       0  1442.7     9.7 1435.74    19.4 1430.61    38.9 1428.49   49.08 1425.67
    58.4 1421.78    68.1 1419.01    77.8 1417.76    95.11417.089   116.7 1415.93
   165.4 1412.62  297.691404.878   298.4 1404.85   311.3 1404.69   313.4 1404.75
     321 1404.96  359.591407.003   398.8 1408.79   437.7 1409.52   476.6  1409.6
   496.1 1409.42     535 1408.18   544.7 1408.03   564.2 1408.03     5721408.569
   573.9  1408.7   583.6 1410.85   680.9 1446.39   700.4 1453.22   719.8 1459.67
#Mann= 8 ,-1 , 0
       0    .016       0   49.08     .08       0    95.1     .06       0
  297.69     .12       0   298.4    .045       0   313.4     .12       0
  359.59     .07       0     572     .12       0
#XS Ineff= 2 , 0
                          465.63         1411.66
Permanent Ineff=
       F       F
Bank Sta=298.4,313.4
XS Rating Curve= 0 ,0
Exp/Cntr=0.3,0.1

Type RM Length L Ch R = 1 ,11461.4 ,629,640.2,651.3
XS GIS Cut Line= 3
     1785062.663      214636.977     1784982.368      214393.921
      1784548.34      213940.362
#Sta/Elev= 30
       0 1438.32    9.721435.012   14.551432.856    28.4 1426.57    37.9 1424.02
    56.9 1422.12    74.11418.501   84.711417.516   180.1 1413.27   373.7 1405.92
   401.7 1404.05   412.9 1403.83   416.7 1404.04  450.551406.837   471.8 1408.91
   481.6 1409.28   520.8 1409.39  574.821408.364   618.9  1407.7   628.7 1408.91
   638.5 1411.75   658.1 1420.29   697.4 1439.08   746.4 1464.82   805.3 1490.66
   815.1 1494.15   824.9 1496.65   844.5 1499.77   864.1 1501.48   883.8 1501.14
#Mann= 9 ,-1 , 0
       0     .12       0    9.72     .06       0   14.55    .016       0
    74.1     .08       0   84.71     .06       0   401.7    .045       0
   416.7     .12       0  450.55     .06       0  574.82     .12       0
Bank Sta=401.7,416.7
XS Rating Curve= 0 ,0
Exp/Cntr=0.3,0.1

Type RM Length L Ch R = 1 ,10821.3 ,571.1,573.4,575.5
XS GIS Cut Line= 3
      1785492.35      214432.984     1785299.208      213738.539
     1785262.316      213515.015
#Sta/Elev= 30
       0 1418.18   11.451417.552    77.9 1414.55   116.9 1413.52   146.1  1411.3
   204.6 1411.15   272.7 1409.16   321.4 1407.12   389.6 1405.92   555.2 1404.43
   603.9 1403.51  608.18 1403.51   615.4 1403.51   630.4 1403.57   642.9 1404.13
   672.1 1407.86   681.8 1408.56   711.1 1409.57   720.8 1410.32   730.2 1412.79
   739.7 1417.59   758.6 1428.65     768 1433.42   796.3 1446.08   843.5 1468.62
   862.4 1476.88   881.3 1484.33   900.2 1491.17     919 1496.84   947.4 1504.76
#Mann= 5 ,-1 , 0
       0    .016       0   11.45     .06       0  608.18     .12       0
   615.4    .045       0   630.4     .12       0
Bank Sta=615.4,630.4
XS Rating Curve= 0 ,0
Exp/Cntr=0.3,0.1

Type RM Length L Ch R = 1 ,10247.9 ,301.1,294.8,288.1
XS GIS Cut Line= 3
     1785943.739      214315.796     1785928.548      214083.591
     1785830.892      213506.334
#Sta/Elev= 30
       0 1421.84    58.2 1417.57    87.3 1415.68   106.6 1414.77  122.841414.353
  156.871413.734   193.9  1412.7   252.2 1411.83     262  1411.3  268.15 1410.59
   281.5 1408.55  292.141407.203     301 1406.76  553.021406.529   574.2 1406.52
     584 1406.14  600.841404.169   613.2 1403.56  617.67 1403.97     623 1404.46
   632.8 1408.32   642.5 1416.23   652.3 1422.94     662  1427.4   671.8 1430.69
   701.1 1439.05   759.6 1453.85   779.1 1457.75   808.4 1462.15   818.2 1464.03
#Mann= 8 ,-1 , 0
       0     .06       0  122.84    .016       0  156.87     .06       0
  268.15     .08       0  292.14     .06       0  553.02     .12       0
  600.84    .045       0  617.67     .12       0
Bank Sta=600.84,617.67
XS Rating Curve= 0 ,0
Exp/Cntr=0.3,0.1

Type RM Length L Ch R = 1 ,9953.1  ,211.7,198.3,185
XS GIS Cut Line= 2
     1786364.746      214077.081     1786060.927      213458.591
#Sta/Elev= 30
       0 1446.65   11.661445.149   25.161443.323    58.2 1436.94   106.8 1425.43
   116.5 1422.84  127.611418.632   135.9 1415.47   145.6 1413.64  174.781413.239
   242.6 1412.16   252.3 1411.36  273.761407.901  364.821406.324  404.311406.642
   446.4 1407.18  457.121406.221   470.91404.125   485.3 1403.51     495 1404.07
   504.7 1406.57   514.4 1411.83   524.1 1417.89   553.2  1434.8   582.3 1449.52
   601.7  1457.8     660 1481.18   669.7 1485.44   679.4  1490.3   689.1    1496
#Mann= 11 ,-1 , 0
       0     .06       0   11.66     .08       0   25.16     .06       0
  127.61    .016       0  174.78     .08       0  273.76     .06       0
  364.82     .12       0  404.31     .06       0  457.12     .12       0
   470.9    .045       0     495     .12       0
#XS Ineff= 2 , 0
          444.99  1409.8
Permanent Ineff=
       F       F
Bank Sta=470.9,495
XS Rating Curve= 0 ,0
Exp/Cntr=0.3,0.1

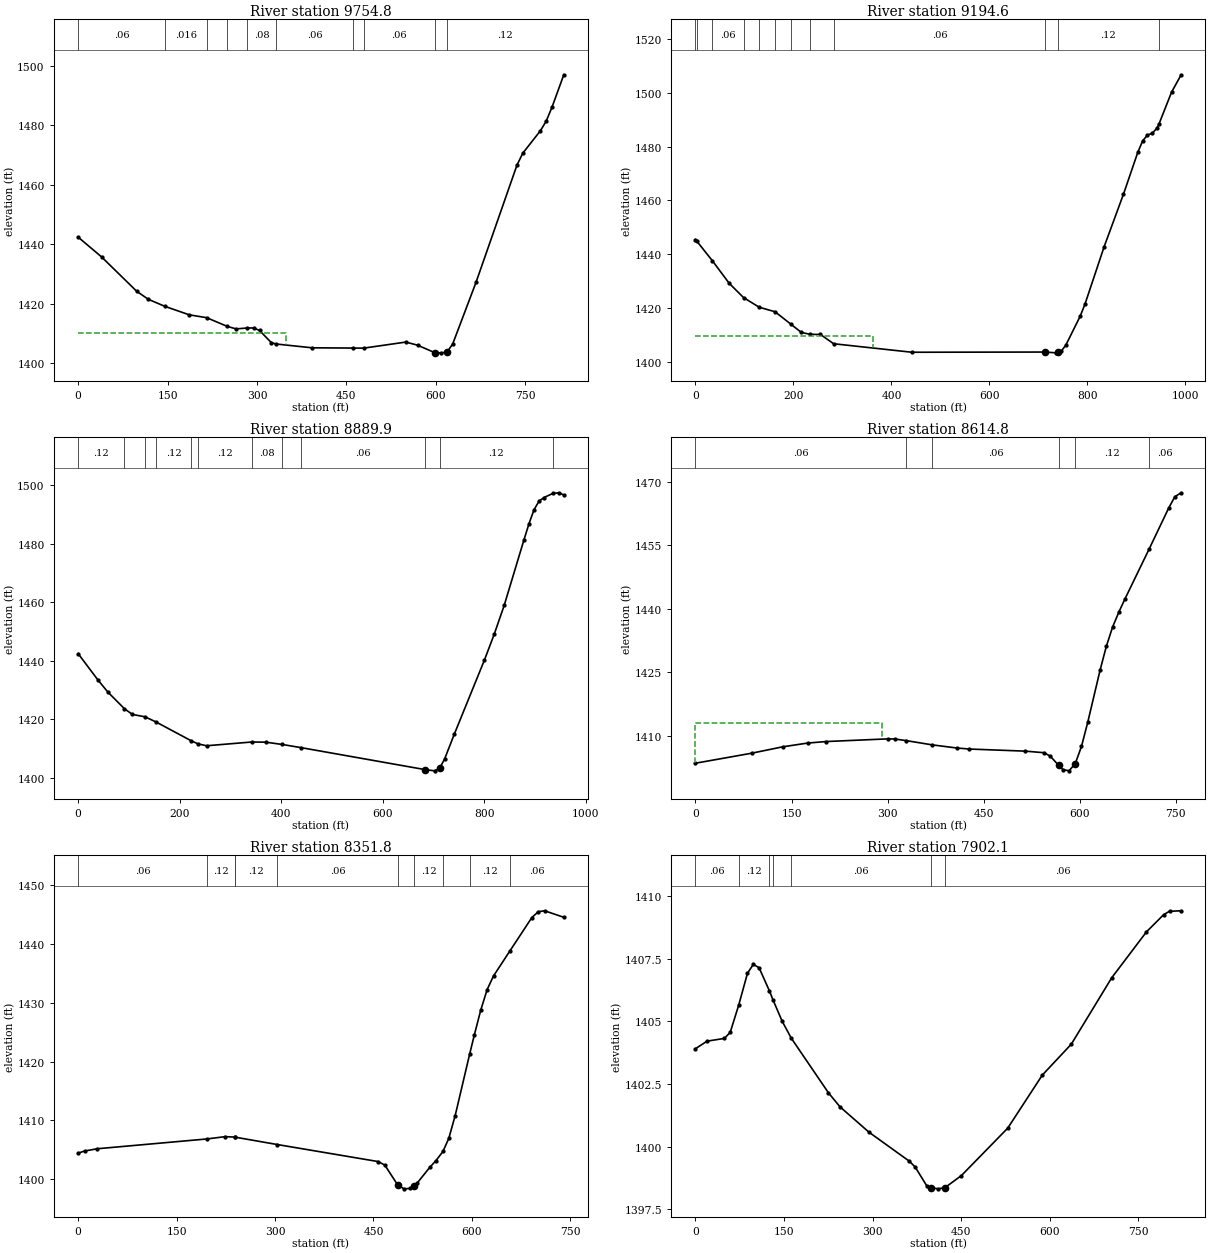
Type RM Length L Ch R = 1 ,9754.8  ,545.8,560.1,574.4
XS GIS Cut Line= 2
     1786824.816      213816.664     1786119.521      213408.678
#Sta/Elev= 30
       0 1442.42    39.3 1435.77    98.2 1424.22   117.8 1421.51   145.4 1419.15
   186.5 1416.29  215.661415.331  250.121412.406     265 1411.56  283.591411.862
   294.5 1411.88   304.3 1411.03     324 1406.97  331.72 1406.49   392.7  1405.2
  461.651405.119  478.98 1405.09   549.7 1407.13   569.4 1406.09   598.8 1403.53
   608.6 1403.51   618.5 1403.69   628.3 1406.43   667.5 1427.19   736.3 1466.66
   746.1 1470.67   775.5 1478.17   785.4 1481.46   795.2  1486.2   814.8 1497.01
#Mann= 10 ,-1 , 0
       0     .06       0   145.4    .016       0  215.66     .08       0
  250.12     .06       0  283.59     .08       0  331.72     .06       0
  461.65     .12       0  478.98     .06       0   598.8    .045       0
   618.5     .12       0
#XS Ineff= 2 , 0
          348.81 1410.14
Permanent Ineff=
       F       F
Bank Sta=598.8,618.5
XS Rating Curve= 0 ,0
Exp/Cntr=0.3,0.1

Type RM Length L Ch R = 1 ,9194.6  ,311.2,304.7,298.2
XS GIS Cut Line= 2
     1786874.729      213742.879     1786475.423      212835.761
#Sta/Elev= 30
       0 1445.43     2.11444.997   34.141437.671    68.7 1429.23   98.231423.873
  130.271420.292  162.311418.648  194.351414.061   215.9 1410.97  233.861410.247
   255.1 1410.19  281.971406.749   441.6 1403.59   713.81403.665     736 1403.37
   738.81403.513   745.8 1403.87   755.6 1406.16     785 1416.95   794.8 1421.43
   834.1 1442.86   873.4  1462.3   902.8 1477.94   912.6 1482.14   922.4 1484.28
   932.2 1484.95     942 1486.89  945.941488.414   971.5 1500.19   991.1 1506.68
#Mann= 12 ,-1 , 0
       0     .06       0     2.1    .016       0   34.14     .06       0
   98.23     .12       0  130.27    .016       0  162.31     .06       0
  194.35     .12       0  233.86     .08       0  281.97     .06       0
   713.8    .045       0   738.8     .12       0  945.94     .06       0
#XS Ineff= 2 , 0
          362.23 1409.53
Permanent Ineff=
       F       F
Bank Sta=713.8,738.8
XS Rating Curve= 0 ,0
Exp/Cntr=0.3,0.1

Type RM Length L Ch R = 1 ,8889.9  ,284.6,275,265.3
XS GIS Cut Line= 3
     1787148.166      213528.036     1787007.107      213113.539
     1786670.736      212718.574
#Sta/Elev= 30
       0 1442.47    38.9 1433.51    58.4 1429.38   91.251423.668     107 1421.72
  131.731420.916  153.481419.151  223.231412.689   236.21411.679     253 1411.04
  342.311412.322   369.7 1412.26  401.721411.487  439.351410.392   682.6 1402.92
   702.1 1402.48   711.9 1403.35   721.7 1406.46   741.3 1415.15     800 1440.16
   819.6 1449.11   839.2 1458.93   878.3 1481.39   888.1 1486.83   897.9 1491.54
   907.7 1494.48   917.5 1495.74  934.971497.121   946.8 1497.36   956.6 1496.62
#Mann= 12 ,-1 , 0
       0     .12       0   91.25    .016       0  131.73     .08       0
  153.48     .12       0  223.23     .06       0   236.2     .12       0
  342.31     .08       0  401.72     .12       0  439.35     .06       0
   682.6    .045       0   711.9     .12       0  934.97     .06       0
Bank Sta=682.6,711.9
XS Rating Curve= 0 ,0
Exp/Cntr=0.3,0.1

Type RM Length L Ch R = 1 ,8614.8  ,273.3,263.1,252.5
XS GIS Cut Line= 2
     1787499.729      212922.567     1786813.965      212599.216
#Sta/Elev= 30
       0 1403.49    87.5 1405.85   136.1 1407.36     175 1408.25   204.1 1408.61
   301.3 1409.25     311 1409.21  328.541408.841  369.621407.825   408.2 1407.08
   427.7 1406.84   515.2 1406.34   544.3 1405.97     554 1405.14   566.91402.999
   573.5    1402   583.2 1401.69   591.91403.215   592.9 1403.39   602.6 1407.44
   612.4 1413.16   631.8 1425.56   641.5 1431.14   651.2 1435.66     661  1439.2
   670.7 1442.36  708.211454.072   738.7 1463.74   748.4 1466.44   758.2 1467.37
#Mann= 6 ,-1 , 0
       0     .06       0  328.54     .12       0  369.62     .06       0
   566.9    .045       0   591.9     .12       0  708.21     .06       0
#XS Ineff= 2 , 0
          290.61 1412.89
Permanent Ineff=
       F       F
Bank Sta=566.9,591.9
XS Rating Curve= 0 ,0
Exp/Cntr=0.3,0.1

Type RM Length L Ch R = 1 ,8351.8  ,435.1,449.7,464.2
XS GIS Cut Line= 2
     1787584.364      212455.987     1786844.347      212460.327
#Sta/Elev= 30
       0 1404.43     9.7 1404.79    29.2 1405.18  196.251406.845     224 1407.24
   238.31407.164  239.561407.143  303.151405.902   457.6 1402.99   467.4 1402.38
   486.9 1399.02   496.6 1398.36   506.3 1398.43   511.9 1398.91   516.1 1399.27
   535.6 1401.99   545.3 1403.17  555.871404.718   564.8 1406.95   574.5 1410.82
  596.54 1421.27   603.7 1424.54   613.4 1428.74   623.2 1432.25   632.9 1434.57
  658.021438.853   691.3  1444.5   701.1  1445.5   710.8 1445.66     740 1444.55
#Mann= 10 ,-1 , 0
       0     .06       0  196.25     .12       0   238.3     .06       0
  239.56     .12       0  303.15     .06       0   486.9    .045       0
   511.9     .12       0  555.87     .06       0  596.54     .12       0
  658.02     .06       0
Bank Sta=486.9,511.9
XS Rating Curve= 0 ,0
Exp/Cntr=0.3,0.1

Type RM Length L Ch R = 1 ,7902.1  ,409.7,400,390.4
XS GIS Cut Line= 2
     1787540.962      212273.695     1786879.069      211785.414
#Sta/Elev= 30
       0 1403.91    19.6 1404.21      49 1404.32    58.8 1404.56   73.071405.636
    88.1 1406.92    97.9 1407.27   107.7 1407.14  125.161406.219  131.681405.835
   146.9    1405  162.321404.326   225.2 1402.15   244.8 1401.59   293.8 1400.58
   362.3 1399.42   372.1 1399.19   391.7 1398.44   399.2 1398.36   411.2 1398.32
  422.791398.372   450.4 1398.85   528.8 1400.74   587.5 1402.86   636.5 1404.09
     705 1406.74   763.8 1408.57   793.1 1409.26   802.9 1409.39   822.5 1409.41
#Mann= 7 ,-1 , 0
       0     .06       0   73.07     .12       0  125.16     .08       0
  131.68     .12       0  162.32     .06       0   399.2    .045       0
  422.79     .06       0
Bank Sta=399.2,422.79
XS Rating Curve= 0 ,0
Exp/Cntr=0.3,0.1