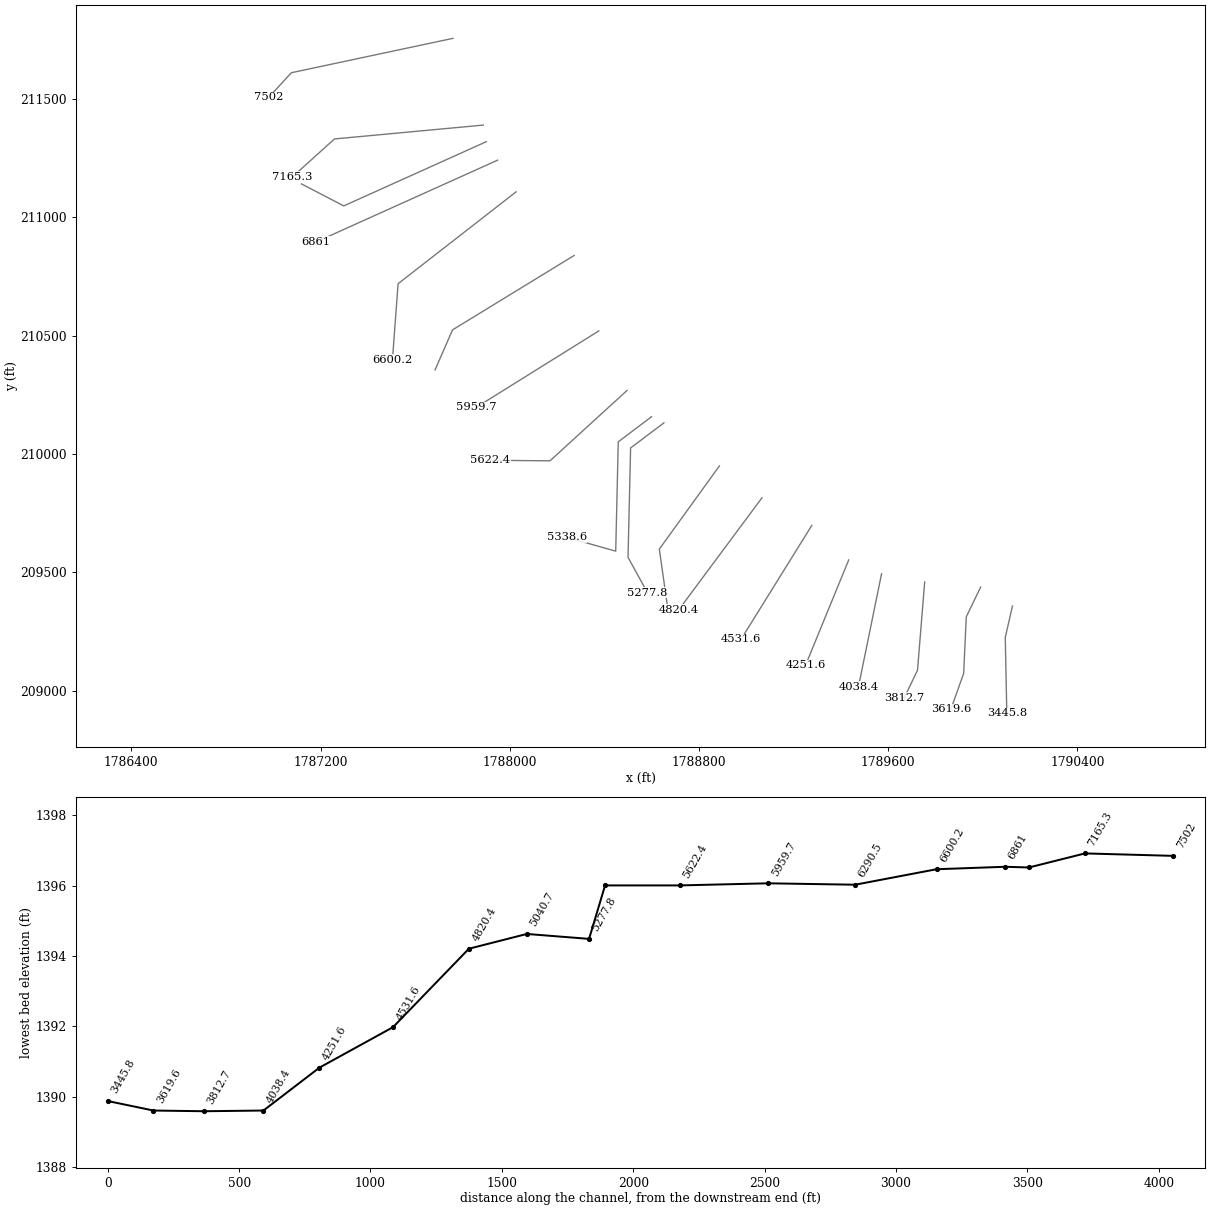
HEC-RAS study BIGRN.prj: BIGRN

--- BIGRN.g01 (geometry) --- (continued)

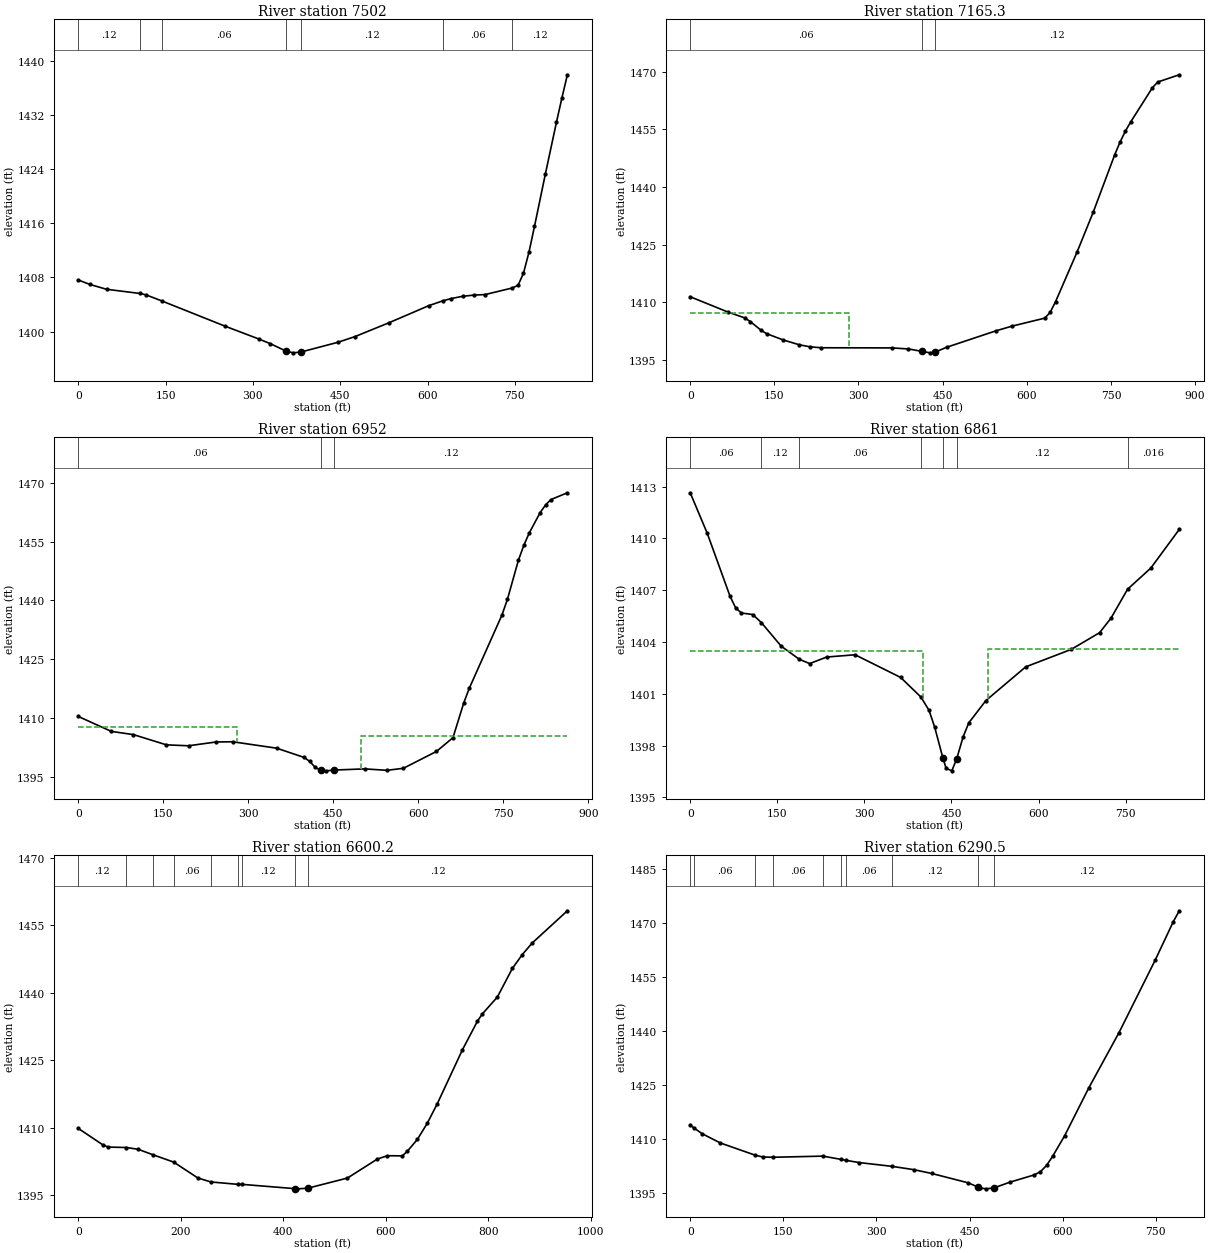
Type RM Length L Ch R = 1 ,7502    ,339.2,336.7,334
XS GIS Cut Line= 3
     1787760.146      211757.202     1787076.552      211611.803
     1786981.066      211507.636
#Sta/Elev= 30
       0 1407.61    19.4 1406.97    48.5 1406.24   106.11405.619   116.5 1405.41
  143.11 1404.53   252.4 1400.78   310.6 1398.88     330  1398.2   357.11397.097
   368.9 1396.85   382.11396.962   446.5 1398.42   475.6 1399.26   533.9  1401.3
   601.8 1403.81  626.111404.532   640.6 1404.87   660.1  1405.2   679.5 1405.38
   698.9 1405.46  745.361406.428   755.4 1406.82   764.8 1408.61   774.2 1411.71
   783.7 1415.53   802.5 1423.31   821.4  1430.9   830.8  1434.5   840.2 1437.93
#Mann= 7 ,-1 , 0
       0     .12       0   106.1     .08       0  143.11     .06       0
   357.1    .045       0   382.1     .12       0  626.11     .06       0
  745.36     .12       0
Bank Sta=357.1,382.1
XS Rating Curve= 0 ,0
Exp/Cntr=0.3,0.1

Type RM Length L Ch R = 1 ,7165.3  ,205.5,213.3,220.5
XS GIS Cut Line= 3
     1787888.184      211390.449     1787258.844      211331.855
     1787080.892      211171.265
#Sta/Elev= 30
       0 1411.49    68.1 1407.47    97.2    1406     107 1405.06   126.4 1402.78
   136.1 1401.91   165.3 1400.29   194.5 1399.01   213.9 1398.48   233.4 1398.24
   359.8  1398.2     389 1397.93  413.41 1397.29   427.9 1396.92   437.2 1397.14
     457 1398.36   544.6 1402.62   573.7 1403.86   632.1 1405.94   641.6 1407.42
   651.2 1410.18   689.6  1423.1   718.4 1433.45   756.7 1448.37   766.3 1451.69
   775.9 1454.56   785.5 1456.98   823.8 1465.77   833.4 1467.28   871.8 1469.16
#Mann= 3 ,-1 , 0
       0     .06       0  413.41    .045       0   437.2     .12       0
#XS Ineff= 2 , 0
          282.77 1407.16
Permanent Ineff=
       F       F
Bank Sta=413.41,437.2
XS Rating Curve= 0 ,0
Exp/Cntr=0.3,0.1

Type RM Length L Ch R = 1 ,6952    ,91.2,91,91.2
XS GIS Cut Line= 3
     1787901.103      211320.373     1787298.247      211048.815
     1787119.087      211141.968
#Sta/Elev= 30
       0 1410.39    58.3 1406.58    97.2 1405.76   155.6 1403.15   194.5 1402.91
   243.1 1403.88   272.3 1403.94     350  1402.3   398.7 1399.93   408.4 1398.92
   418.1 1397.41   427.8 1396.64   437.6 1396.52  451.291396.718   505.6 1397.02
   544.5 1396.65   573.7 1397.17     632 1401.46   661.2 1404.98   680.4 1413.91
     690 1417.59   747.7 1436.27   757.4  1440.3   776.6 1450.19   786.2 1454.02
   795.8 1457.18     815 1462.37   824.7 1464.36   834.3 1465.72   863.1 1467.44
#Mann= 3 ,-1 , 0
       0     .06       0   427.8    .045       0  451.29     .12       0
#XS Ineff= 2 , 0
          279.67  1407.7  498.45         1405.41
Permanent Ineff=
       F       F
Bank Sta=427.8,451.29
XS Rating Curve= 0 ,0
Exp/Cntr=0.3,0.1

Type RM Length L Ch R = 1 ,6861    ,255.4,260.8,266.2
XS GIS Cut Line= 2
     1787948.846      211242.248      1787180.82      210896.288
#Sta/Elev= 30
       0 1412.64    29.4 1410.29    68.6 1406.65    78.4 1405.97    88.2 1405.68
   107.7 1405.59  122.551405.125   156.7 1403.76  187.84    1403   205.7 1402.75
   235.1 1403.13     284 1403.26   362.4 1401.95  397.421400.812   411.4 1400.04
   421.2 1399.06  435.361397.267   440.8 1396.69   450.6 1396.54   459.11397.243
   470.2 1398.52   479.9 1399.32   509.3 1400.61   577.9 1402.56   656.2 1403.57
   705.2 1404.54   724.8 1405.38  753.371407.056   793.4 1408.28   842.4 1410.52
#Mann= 7 ,-1 , 0
       0     .06       0  122.55     .12       0  187.84     .06       0
  397.42     .12       0  435.36    .045       0   459.1     .12       0
  753.37    .016       0
#XS Ineff= 2 , 0
          401.44 1403.48   512.9         1403.57
Permanent Ineff=
       F       F
Bank Sta=435.36,459.1
XS Rating Curve= 0 ,0
Exp/Cntr=0.3,0.1

Type RM Length L Ch R = 1 ,6600.2  ,312.2,309.7,307.1
XS GIS Cut Line= 3
     1788027.073      211108.331     1787527.941      210719.876
     1787504.069      210398.695
#Sta/Elev= 30
       0 1409.88    48.6 1406.18    58.4 1405.74   93.951405.645   116.8 1405.25
  144.991404.064  186.091402.411   233.5 1398.87  258.951397.997  311.121397.471
  318.91 1397.47   422.61396.514   427.6 1396.47   447.6  1396.6   525.4 1398.87
   583.8 1403.09   603.3 1403.82   632.5 1403.79   642.2 1404.81   661.8 1407.44
   681.3 1411.06   700.8 1415.39   749.6  1427.3   778.9 1433.65   788.6  1435.3
   817.9 1439.04   847.2 1445.39   866.7 1448.49   886.2 1451.07   954.6  1458.2
#Mann= 9 ,-1 , 0
       0     .12       0   93.95     .08       0  144.99     .12       0
  186.09     .06       0  258.95     .12       0  311.12     .06       0
  318.91     .12       0   422.6    .045       0   447.6     .12       0
Bank Sta=422.6,447.6
XS Rating Curve= 0 ,0
Exp/Cntr=0.3,0.1

Type RM Length L Ch R = 1 ,6290.5  ,330.5,330.8,330.9
XS GIS Cut Line= 3
     1788272.298      210839.234     1787757.975      210524.563
     1787684.191      210355.293
#Sta/Elev= 30
       0 1413.77     6.51412.892    19.4 1411.34    48.6 1408.78   104.91405.371
   116.7 1404.89  133.391404.807  213.591405.129  242.451404.234  251.191403.943
   272.3 1403.33  324.531402.295   359.8 1401.37     389  1400.3   447.4 1397.71
  463.321396.546   466.8 1396.28   476.5 1396.03  488.691396.265   515.4 1397.91
   554.3 1399.92     564  1400.8   573.8 1402.52   583.5 1405.03     603 1410.79
   641.8 1424.07   690.4 1439.41   748.7 1459.57   777.9 1470.28   787.6 1473.34
#Mann= 10 ,-1 , 0
       0     .12       0     6.5     .06       0   104.9     .12       0
  133.39     .06       0  213.59     .08       0  242.45     .12       0
  251.19     .06       0  324.53     .12       0  463.32    .045       0
  488.69     .12       0
Bank Sta=463.32,488.69
XS Rating Curve= 0 ,0
Exp/Cntr=0.3,0.1

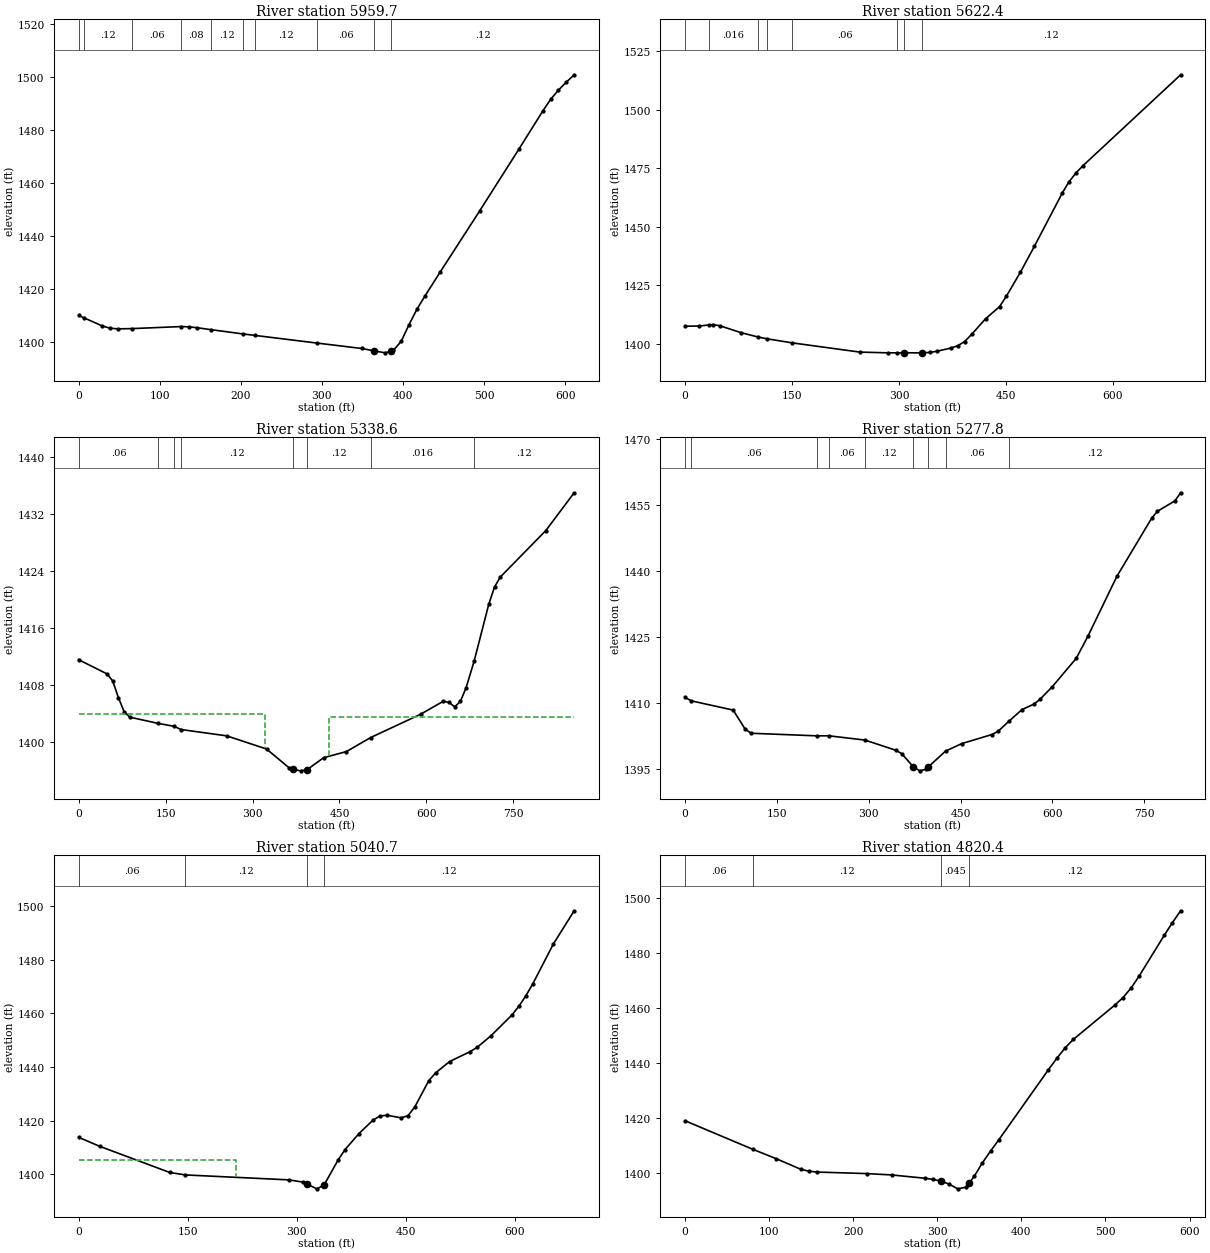
Type RM Length L Ch R = 1 ,5959.7  ,333.1,337.3,341.3
XS GIS Cut Line= 2
     1788376.465      210520.223     1787857.802      210196.873
#Sta/Elev= 30
       0 1410.22    6.041409.342    29.1 1406.22    38.8 1405.35    48.5 1405.11
   65.631405.208  126.841405.982   135.8 1405.88   145.5 1405.57  163.041404.819
  203.19 1403.18  216.931402.659  294.041399.755   349.3 1397.71  364.131396.815
   378.4 1396.07  385.771396.754   388.1 1396.97   397.8 1400.38   407.5 1406.68
   417.2 1412.48   426.9 1417.38   446.3 1426.71   494.8 1449.67   543.3 1473.01
   572.4 1487.22   582.1 1491.62   591.8 1495.15   601.5 1498.13   611.2 1500.92
#Mann= 10 ,-1 , 0
       0     .06       0    6.04     .12       0   65.63     .06       0
  126.84     .08       0  163.04     .12       0  203.19     .06       0
  216.93     .12       0  294.04     .06       0  364.13    .045       0
  385.77     .12       0
Bank Sta=364.13,385.77
XS Rating Curve= 0 ,0
Exp/Cntr=0.3,0.1

Type RM Length L Ch R = 1 ,5622.4  ,259.3,283.7,305.8
XS GIS Cut Line= 3
     1788495.823      210268.487     1788170.302      209971.178
     1787916.396      209973.348
#Sta/Elev= 30
       0  1407.4    19.6 1407.48   33.181407.922    39.2  1408.1      49 1407.56
    78.4 1404.65  101.66 1402.82  114.431402.035  149.55  1400.3   244.9 1396.33
   284.1 1396.01  297.47 1396.01   307.2 1396.01   332.2 1396.01   342.9 1396.18
   352.7 1396.67   372.3 1398.03   382.1 1399.03   391.9 1400.83   401.7 1403.89
   421.3 1410.58   440.9 1415.76   450.6  1420.3   470.2 1430.52   489.7 1441.56
   528.8 1464.33   538.5 1469.26   548.3 1473.04     558 1476.09   694.8 1514.93
#Mann= 8 ,-1 , 0
       0     .12       0   33.18    .016       0  101.66     .08       0
  114.43     .12       0  149.55     .06       0  297.47     .12       0
   307.2    .045       0   332.2     .12       0
Bank Sta=307.2,332.2
XS Rating Curve= 0 ,0
Exp/Cntr=0.3,0.1

Type RM Length L Ch R = 1 ,5338.6  ,66.9,60.9,57.1
XS GIS Cut Line= 4
     1788599.989       210157.81      1788458.93      210051.473
      1788448.08      209589.234     1788240.325      209648.044
#Sta/Elev= 30
       0  1411.6    49.1  1409.6    58.9  1408.6    68.7 1406.26    78.5 1404.31
    88.3 1403.54  137.241402.663  165.031402.247  176.461401.806   255.4 1400.92
   324.2 1399.07   363.6  1396.4   369.41396.205   383.2 1396.01   394.41396.188
   422.6 1397.85   461.9 1398.71  503.721400.676   589.8 1403.94   629.2 1405.77
     639  1405.6   648.8 1404.99   658.6 1405.74   668.5 1407.68   682.31411.396
   707.7 1419.42   717.5 1421.79   727.4 1423.19   805.9  1429.7   854.9 1435.01
#Mann= 8 ,-1 , 0
       0     .06       0  137.24    .016       0  165.03     .08       0
  176.46     .12       0   369.4    .045       0   394.4     .12       0
  503.72    .016       0   682.3     .12       0
#XS Ineff= 2 , 0
          320.95 1404.02  431.37         1403.51
Permanent Ineff=
       F       F
Bank Sta=369.4,394.4
XS Rating Curve= 0 ,0
Exp/Cntr=0.3,0.1

Type RM Length L Ch R = 1 ,5277.8  ,250.5,237,223.2
XS GIS Cut Line= 4
     1788652.073      210131.768     1788511.014      210025.432
     1788500.163      209563.192     1788582.339      209413.669
#Sta/Elev= 30
       0 1411.18   10.141410.412    78.5 1408.31    98.1 1403.98     108 1403.04
  215.721402.449  234.731402.464  293.931401.487   343.9 1399.19   353.7 1398.42
   372.61395.451   383.2 1394.49   393.1 1394.84   397.61395.414  425.551398.983
   452.1 1400.69   501.3 1402.75   511.1 1403.45  529.161405.787   550.5 1408.44
   570.2 1409.68     580  1410.8   599.7  1413.6     639 1420.08     658 1425.08
   705.4 1438.73   762.2 1451.95   771.7 1453.54   800.2 1455.91   809.6 1457.75
#Mann= 9 ,-1 , 0
       0     .08       0   10.14     .06       0  215.72     .12       0
  234.73     .06       0  293.93     .12       0   372.6    .045       0
   397.6     .12       0  425.55     .06       0  529.16     .12       0
Bank Sta=372.6,397.6
XS Rating Curve= 0 ,0
Exp/Cntr=0.3,0.1

Type RM Length L Ch R = 1 ,5040.7  ,220.7,220.4,220
XS GIS Cut Line= 3
     1788886.448      209949.477     1788632.541      209597.914
     1788667.264      209352.688
#Sta/Elev= 30
       0 1413.83    28.9 1410.47   125.3 1400.72  146.811399.812   289.1 1397.97
   308.4 1397.13  313.78 1396.39   327.7 1394.63   337.3    1396   356.6 1405.31
   366.2 1409.24   385.5 1415.22   404.8 1420.25   414.4 1421.76     424 1422.05
   443.2 1421.09   452.7 1421.83   462.2 1425.14   481.3 1434.88   490.8 1437.81
   509.9 1442.03   538.4 1445.75     548 1447.36     567 1451.67   595.6 1459.34
   605.1 1462.58   614.6 1466.42   624.2 1470.88   652.8 1485.88   681.3  1498.2
#Mann= 4 ,-1 , 0
       0     .06       0  146.81     .12       0  313.78    .045       0
   337.3     .12       0
#XS Ineff= 2 , 0
          216.72 1405.34
Permanent Ineff=
       F       F
Bank Sta=313.78,337.3
XS Rating Curve= 0 ,0
Exp/Cntr=0.3,0.1

Type RM Length L Ch R = 1 ,4820.4  ,286.8,288.8,290.7
XS GIS Cut Line= 2
     1789066.569      209814.928     1788715.007      209341.838
#Sta/Elev= 30
       0 1418.99   80.351408.624   108.1 1405.22   137.5 1401.35   147.4 1400.62
   157.2 1400.32   216.1 1399.76   245.6 1399.27   284.9 1398.08   294.7 1397.66
   304.5 1397.01   314.4 1395.88   324.2 1394.21     334  1394.8   337.7 1396.28
   343.8 1398.72   353.6 1403.68   363.5 1408.05   373.3 1412.13   432.2  1437.6
   442.1 1441.71   451.9 1445.49   461.7  1448.6   510.8 1461.02   520.6 1463.75
   530.5 1467.33   540.3  1471.8   569.8 1486.45   579.6 1491.11   589.4 1495.44
#Mann= 4 ,-1 , 0
       0     .06       0   80.35     .12       0   304.5    .045       0
   337.7     .12       0
Bank Sta=304.5,337.7
XS Rating Curve= 0 ,0
Exp/Cntr=0.3,0.1

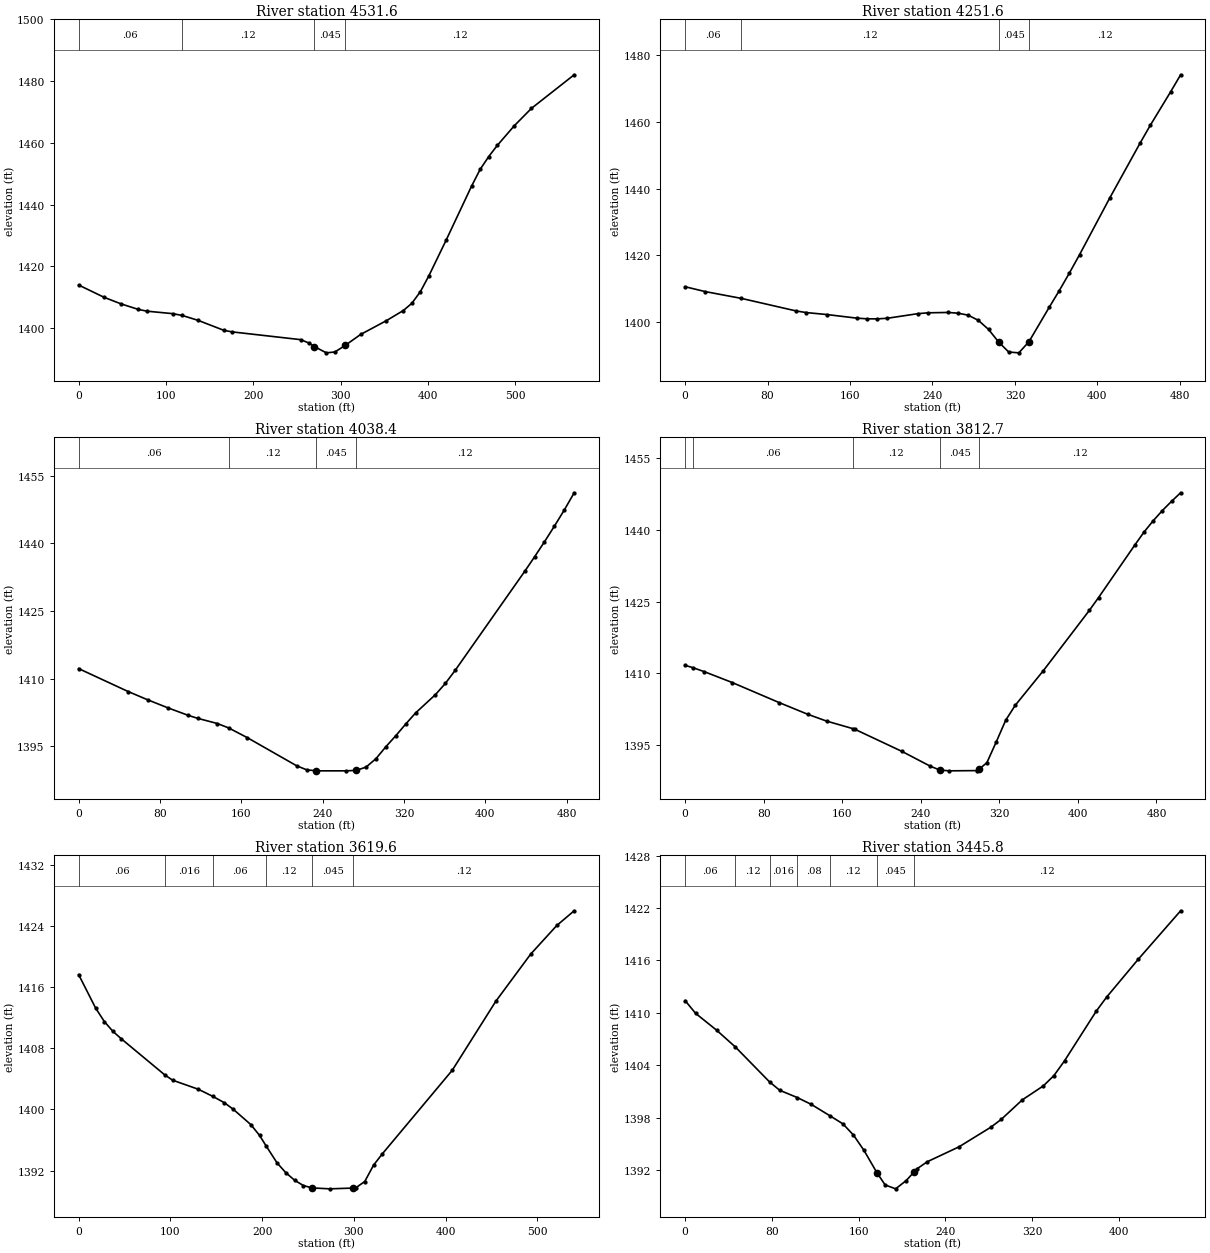
Type RM Length L Ch R = 1 ,4531.6  ,274.8,280,284.9
XS GIS Cut Line= 2
     1789277.073      209697.741     1788977.594       209215.97
#Sta/Elev= 30
       0 1413.95    29.3 1409.95    48.9 1407.81    68.5 1406.04    78.2 1405.48
   107.6 1404.68  118.471404.101   136.9 1402.49   166.3 1399.27     176 1398.76
   254.3 1396.25   264.1  1395.1     2701393.993   283.6 1391.98   293.4 1392.26
     3051394.359   322.8 1397.93   352.1 1402.37   371.7 1405.69   381.4 1408.01
   391.2 1411.78     401 1416.96   420.6 1428.42   449.9 1446.03   459.7 1451.44
   469.5 1455.58   479.2 1459.16   498.8 1465.57   518.4 1471.19   567.3 1482.07
#Mann= 4 ,-1 , 0
       0     .06       0  118.47     .12       0     270    .045       0
     305     .12       0
Bank Sta=270,305
XS Rating Curve= 0 ,0
Exp/Cntr=0.3,0.1

Type RM Length L Ch R = 1 ,4251.6  ,210.1,213.2,216.6
XS GIS Cut Line= 2
     1789433.323      209552.341     1789251.031      209107.463
#Sta/Elev= 30
       0 1410.62    19.6 1409.16   54.641407.127   107.9 1403.36   117.7 1402.88
   137.4  1402.3   166.8 1401.21   176.6 1401.02   186.4    1401   196.2 1401.18
   225.7 1402.55   235.5 1402.81   255.1 1402.92   264.9  1402.7   274.7  1402.1
   284.5 1400.56   294.4 1397.85   304.2 1394.07     314 1391.07   323.8 1390.83
   333.6 1394.15   353.2 1404.42     363 1409.43   372.8 1414.69   382.7  1420.2
   412.1 1437.23   441.5 1453.64   451.3 1458.92     471 1468.93   480.8 1474.07
#Mann= 4 ,-1 , 0
       0     .06       0   54.64     .12       0   304.2    .045       0
   333.6     .12       0
Bank Sta=304.2,333.6
XS Rating Curve= 0 ,0
Exp/Cntr=0.3,0.1

Type RM Length L Ch R = 1 ,4038.4  ,222.8,225.6,228.2
XS GIS Cut Line= 2
     1789572.212      209493.748     1789474.555      209016.317
#Sta/Elev= 29
       0 1412.25    48.7 1407.17    68.2 1405.31    87.7 1403.57   107.2 1401.94
     117 1401.24   136.4 1400.09  147.491399.115   165.7 1396.98   214.4 1390.73
   224.2 1389.84   233.9 1389.61   263.2 1389.61   272.9 1389.71   282.6 1390.43
   292.4 1392.31   302.1 1394.94   311.9 1397.39   321.6 1399.96   331.4 1402.44
   350.9 1406.49   360.6 1408.96   370.4  1411.9   438.6 1433.76   448.3 1436.98
   458.1 1440.33   467.8 1443.77   477.6 1447.37   487.3 1451.18
#Mann= 4 ,-1 , 0
       0     .06       0  147.49     .12       0   233.9    .045       0
   272.9     .12       0
Bank Sta=233.9,272.9
XS Rating Curve= 0 ,0
Exp/Cntr=0.3,0.1

Type RM Length L Ch R = 1 ,3812.7  ,192.3,193.1,193.9
XS GIS Cut Line= 3
     1789754.503      209459.025     1789724.121      209085.761
     1789667.698      208968.574
#Sta/Elev= 28
       0 1411.68       81411.188    19.2 1410.38      48 1408.08      96 1403.86
   124.8 1401.44     144 1400.01  170.881398.424   172.8  1398.3   220.9 1393.65
   249.7 1390.56   259.3 1389.76   268.9 1389.59   297.7 1389.64   299.7 1389.99
   307.3  1391.3   316.9 1395.67   326.5  1400.2   336.1 1403.29   364.9 1410.59
   411.7  1423.2     421 1425.87   458.1 1436.92   467.4 1439.61   476.7 1441.96
     486 1444.09   495.3 1446.01   504.6 1447.81
#Mann= 5 ,-1 , 0
       0    .016       0       8     .06       0  170.88     .12       0
   259.3    .045       0   299.7     .12       0
Bank Sta=259.3,299.7
XS Rating Curve= 0 ,0
Exp/Cntr=0.3,0.1

Type RM Length L Ch R = 1 ,3619.6  ,172.4,173.8,175.3
XS GIS Cut Line= 4
     1789991.048      209437.324     1789930.285      209311.456
     1789919.434      209072.741      1789865.18      208920.831
#Sta/Elev= 30
       0 1417.64    18.6 1413.24      28  1411.5    37.3 1410.22    46.6 1409.23
   93.871404.516   102.5 1403.82   130.4 1402.64  146.411401.697   158.9 1400.87
   168.4 1400.03   187.6 1398.02   197.1 1396.61  204.051395.271   216.2 1393.01
   225.8 1391.72   235.4 1390.73   244.9 1390.04   254.5 1389.73   273.6 1389.61
   298.8 1389.71   302.3 1389.77   311.8 1390.57   321.4 1392.71   330.9 1394.18
   407.2 1405.13   454.6 1414.15   492.6 1420.32   521.1 1424.07     540 1425.99
#Mann= 6 ,-1 , 0
       0     .06       0   93.87    .016       0  146.41     .06       0
  204.05     .12       0   254.5    .045       0   298.8     .12       0
Bank Sta=254.5,298.8
XS Rating Curve= 0 ,0
Exp/Cntr=0.3,0.1

Type RM Length L Ch R = 1 ,3445.8  ,177.7,177.5,177.3
XS GIS Cut Line= 3
     1790125.597      209357.029     1790095.215       209224.65
     1790101.725       208903.47
#Sta/Elev= 30
       0 1411.41     9.7 1409.95    29.1 1408.02   46.471406.091   77.911402.108
    87.3 1401.15  103.381400.324   116.4 1399.54  133.581398.236   145.6 1397.31
   155.3 1396.03     165 1394.28  176.871391.739   184.5 1390.33   194.2 1389.88
     204 1390.83  210.76 1391.75   213.7 1392.15   223.4 1392.98   252.6 1394.68
   281.8 1396.91   291.6 1397.82     311 1400.05   330.5 1401.66   340.2 1402.83
     350 1404.52   379.2 1410.19   388.9 1411.82   418.1 1416.15   457.1 1421.68
#Mann= 7 ,-1 , 0
       0     .06       0   46.47     .12       0   77.91    .016       0
  103.38     .08       0  133.58     .12       0  176.87    .045       0
  210.76     .12       0
Bank Sta=176.87,210.76
XS Rating Curve= 0 ,0
Exp/Cntr=0.3,0.1