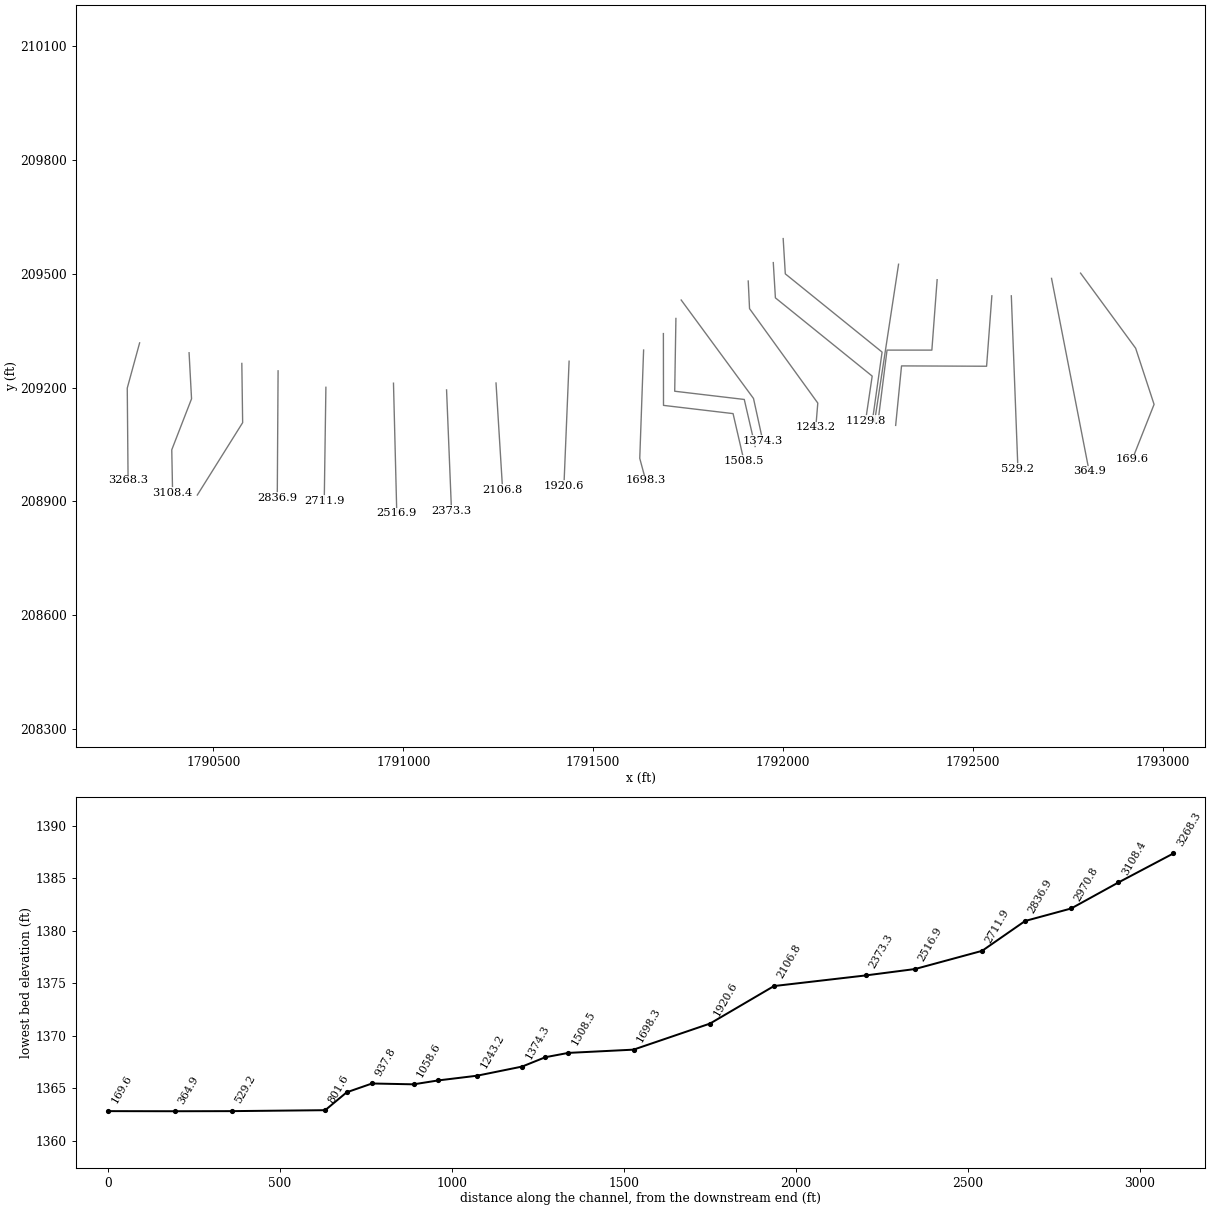
HEC-RAS study BIGRN.prj: BIGRN

--- BIGRN.g01 (geometry) --- (continued)

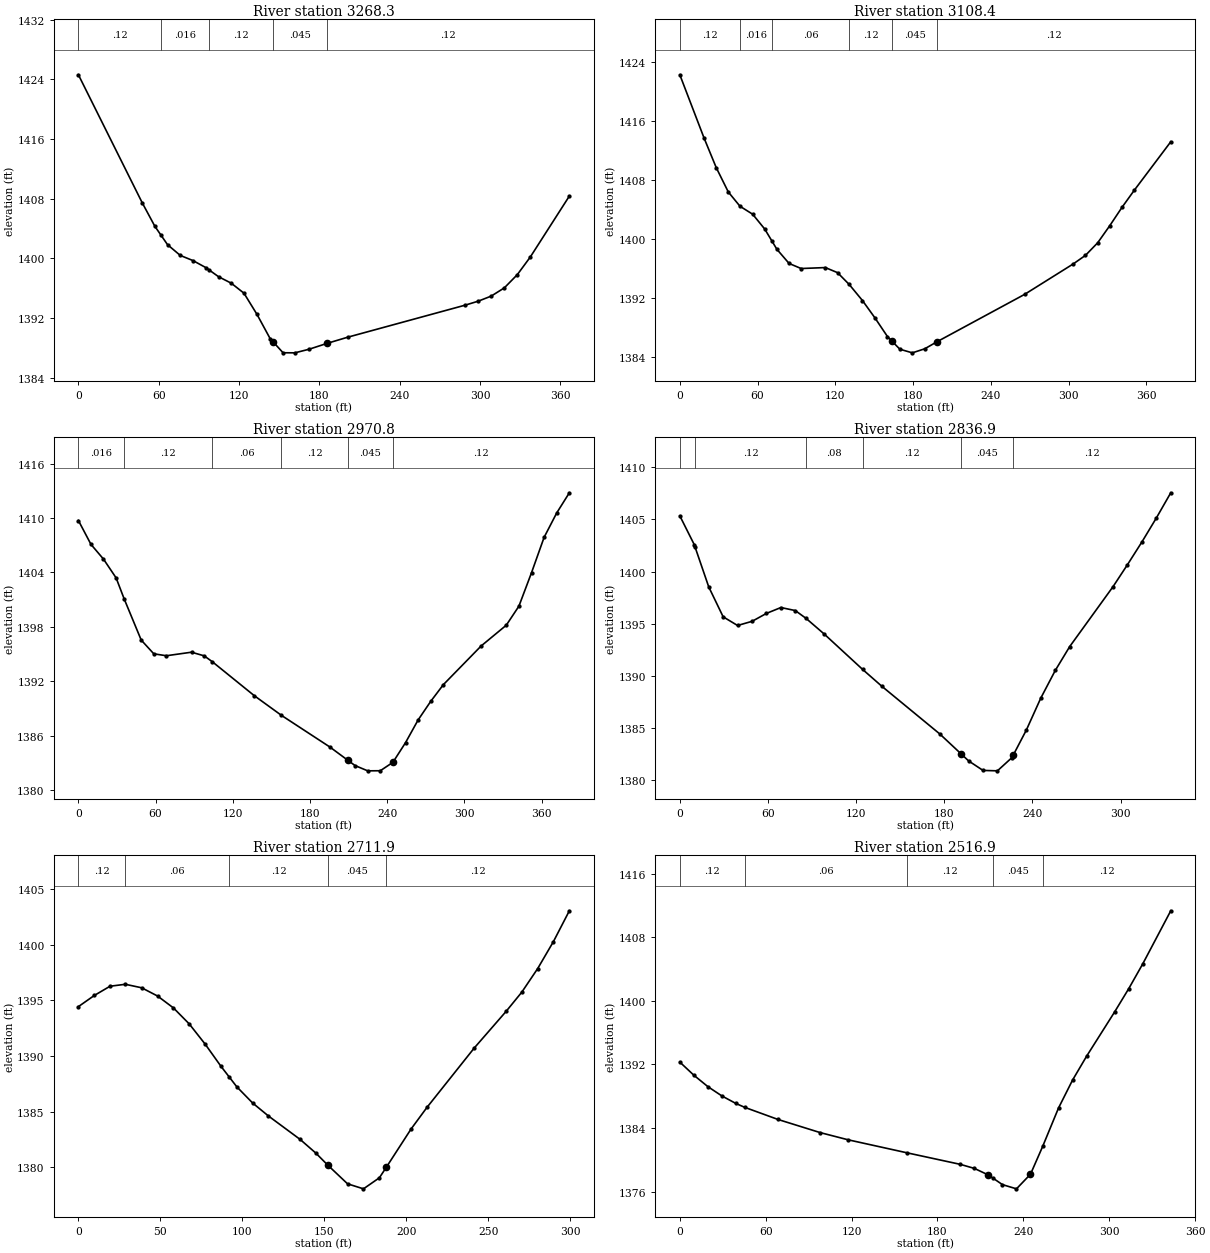
Type RM Length L Ch R = 1 ,3268.3  ,168.3,159.8,151.3
XS GIS Cut Line= 3
     1790305.719      209317.966     1790273.166      209198.609
     1790275.337      208955.553
#Sta/Elev= 27
       0  1424.6    47.6 1407.48    57.1 1404.31   61.681403.119    66.6 1401.84
    76.1  1400.4    85.6 1399.71    95.2 1398.77   97.631398.458   104.7 1397.55
   114.2 1396.68   123.7 1395.34   133.4 1392.51   143.2 1389.27  145.341388.848
   152.9 1387.36   161.7 1387.35   172.3 1387.83  185.961388.628   201.5 1389.46
     289 1393.74   298.7 1394.27   308.4 1394.95   318.2 1396.05   327.9 1397.82
   337.6 1400.18   366.8 1408.35
#Mann= 5 ,-1 , 0
       0     .12       0   61.68    .016       0   97.63     .12       0
  145.34    .045       0  185.96     .12       0
Bank Sta=145.34,185.96
XS Rating Curve= 0 ,0
Exp/Cntr=0.3,0.1

Type RM Length L Ch R = 1 ,3108.4  ,141.9,137.7,133.3
XS GIS Cut Line= 4
     1790435.927      209291.925     1790442.437      209170.397
     1790390.354      209035.848     1790392.524      208923.001
#Sta/Elev= 30
       0 1422.32    18.7 1413.74    28.1 1409.72    37.4 1406.42   46.431404.479
    56.2  1403.4    65.5 1401.39   70.891399.813    74.9 1398.64    84.3 1396.72
    93.6 1396.03   112.3 1396.16   121.7 1395.47  130.641393.878   140.9 1391.69
   150.6 1389.32   160.2  1386.8   163.91386.136   169.8 1385.08   179.4 1384.59
     189 1385.14   198.6 1386.11     266 1392.52   303.6 1396.66     313 1397.82
   322.4 1399.52   331.8 1401.86   341.2 1404.34   350.6 1406.64   378.8 1413.23
#Mann= 6 ,-1 , 0
       0     .12       0   46.43    .016       0   70.89     .06       0
  130.64     .12       0   163.9    .045       0   198.6     .12       0
Bank Sta=163.9,198.6
XS Rating Curve= 0 ,0
Exp/Cntr=0.3,0.1

Type RM Length L Ch R = 1 ,2970.8  ,121.3,133.9,146.4
XS GIS Cut Line= 3
     1790574.816      209263.713     1790576.986      209107.463
     1790457.628      208916.491
#Sta/Elev= 30
       0 1409.73     9.8 1407.09    19.5 1405.47    29.3  1403.4   35.521401.096
    48.8 1396.54    58.6 1395.02    68.4 1394.81    87.9  1395.2    97.7  1394.8
  103.941394.163   136.7  1390.4  157.79 1388.23   195.4 1384.74  209.421383.271
     215 1382.69   224.8 1382.11   234.6 1382.12   244.4 1383.05   254.2 1385.22
     264 1387.73   273.8 1389.78   283.6 1391.62   312.9 1395.88   332.5 1398.18
   342.3 1400.28   352.1 1403.97   361.9 1407.88   371.7 1410.57   381.5 1412.79
#Mann= 6 ,-1 , 0
       0    .016       0   35.52     .12       0  103.94     .06       0
  157.79     .12       0  209.42    .045       0   244.4     .12       0
Bank Sta=209.42,244.4
XS Rating Curve= 0 ,0
Exp/Cntr=0.3,0.1

Type RM Length L Ch R = 1 ,2836.9  ,125.1,125,124.8
XS GIS Cut Line= 2
     1790670.302      209244.182     1790668.132       208909.98
#Sta/Elev= 30
       0 1405.34     9.8 1402.59    10.31402.385    19.7 1398.53    29.5 1395.67
    39.3 1394.84    49.2 1395.24      59    1396    68.8 1396.56    78.6 1396.27
   85.95 1395.52    98.3 1394.02  124.441390.632   137.6 1389.01   176.9 1384.46
  191.711382.514   196.6 1381.87   206.4 1380.96   216.2 1380.92   226.1 1382.19
  227.061382.448   235.9 1384.83   245.7 1387.88   255.6 1390.54   265.4 1392.82
   294.9 1398.56   304.7 1400.66   314.6 1402.85   324.4 1405.14   334.2 1407.55
#Mann= 6 ,-1 , 0
       0    .016       0    10.3     .12       0   85.95     .08       0
  124.44     .12       0  191.71    .045       0  227.06     .12       0
Bank Sta=191.71,227.06
XS Rating Curve= 0 ,0
Exp/Cntr=0.3,0.1

Type RM Length L Ch R = 1 ,2711.9  ,193.9,195,195.8
XS GIS Cut Line= 2
      1790796.17      209200.779      1790791.83        208901.3
#Sta/Elev= 29
       0 1394.43     9.7 1395.43    19.3 1396.26   28.661396.434    38.6 1396.12
    48.3 1395.38      58 1394.31    67.6 1392.88    77.3 1391.07      87 1389.07
   92.081388.102    96.6 1387.24   106.3 1385.78   115.9 1384.62   135.3 1382.51
   144.9 1381.28  152.151380.204   164.2 1378.53   173.9 1378.08   183.6 1379.07
  187.751379.995   202.9 1383.44   212.6 1385.38   241.5 1390.72   260.9    1394
   270.5 1395.73   280.2 1397.85   289.8 1400.27   299.5 1403.03
#Mann= 5 ,-1 , 0
       0     .12       0   28.66     .06       0   92.08     .12       0
  152.15    .045       0  187.75     .12       0
Bank Sta=152.15,187.75
XS Rating Curve= 0 ,0
Exp/Cntr=0.3,0.1

Type RM Length L Ch R = 1 ,2516.9  ,143.4,143.7,144
XS GIS Cut Line= 2
     1790974.121      209211.629     1790982.802      208868.748
#Sta/Elev= 25
       0  1392.3     9.8 1390.65    19.6 1389.21    29.4 1388.04    39.2 1387.09
   45.521386.593    68.6 1385.08      98 1383.43   117.6 1382.52  158.881380.877
     196 1379.43   205.8 1378.92   215.6 1378.09   218.51377.732   225.4 1376.88
   235.2 1376.35     245 1378.19   253.51381.685   264.6 1386.53   274.4 1390.04
   284.2 1393.04   303.8 1398.62   313.6 1401.53   323.4 1404.65     343 1411.34
#Mann= 5 ,-1 , 0
       0     .12       0   45.52     .06       0  158.88     .12       0
   218.5    .045       0   253.5     .12       0
Bank Sta=215.6,245
XS Rating Curve= 0 ,0
Exp/Cntr=0.3,0.1

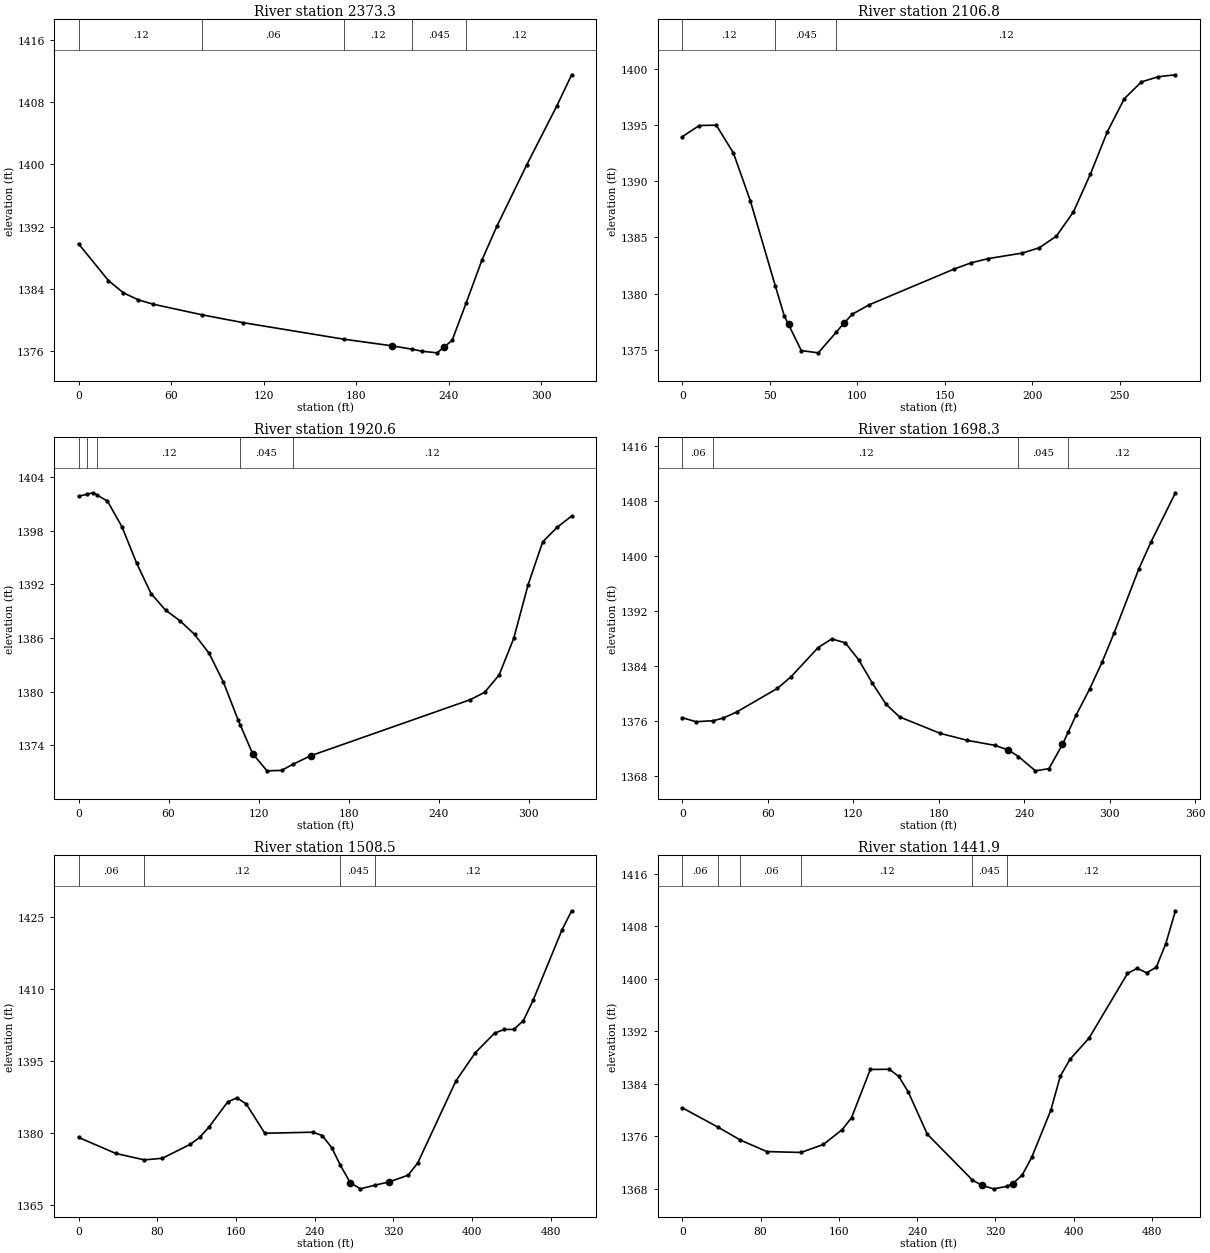
Type RM Length L Ch R = 1 ,2373.3  ,266.3,266.5,266.2
XS GIS Cut Line= 2
     1791113.878      209193.834     1791126.899       208874.39
#Sta/Elev= 20
       0 1389.78    19.4 1385.04    29.1 1383.46    38.8 1382.56    48.4    1382
   80.381380.625   106.6 1379.63  171.841377.502   203.4 1376.64   216.21376.211
   222.8 1375.94   232.5 1375.74   237.2 1376.52   242.2 1377.34   251.2  1382.1
   261.6  1387.7   271.3 1392.06   290.6 1399.94     310 1407.48   319.7 1411.53
#Mann= 5 ,-1 , 0
       0     .12       0   80.38     .06       0  171.84     .12       0
   216.2    .045       0   251.2     .12       0
Bank Sta=203.4,237.2
XS Rating Curve= 0 ,0
Exp/Cntr=0.3,0.1

Type RM Length L Ch R = 1 ,2106.8  ,188.6,186.1,183.6
XS GIS Cut Line= 2
     1791244.087      209212.063     1791261.448      208930.813
#Sta/Elev= 27
       0 1393.95     9.7 1394.94    19.4 1394.97    29.2  1392.5    38.9 1388.23
    53.11380.702    58.3    1378   60.68 1377.25      68 1374.93    77.7 1374.73
    88.11376.591   92.26 1377.35    97.2 1378.17   106.9 1379.01   155.5 1382.19
   165.2 1382.74   174.9 1383.11   194.3  1383.6     204 1384.07   213.8 1385.11
   223.5 1387.26   233.2 1390.62   242.9 1394.39   252.6 1397.33   262.4 1398.82
   272.1 1399.28   281.8 1399.45
#Mann= 3 ,-1 , 0
       0     .12       0    53.1    .045       0    88.1     .12       0
Bank Sta=60.68,92.26
XS Rating Curve= 0 ,0
Exp/Cntr=0.3,0.1

Type RM Length L Ch R = 1 ,1920.6  ,222.4,222.4,222.3
XS GIS Cut Line= 2
     1791436.506      209269.572     1791422.906       208941.23
#Sta/Elev= 28
       0 1401.85    5.891402.087     9.7 1402.24   12.451401.974    19.3 1401.31
      29 1398.42    38.7 1394.39    48.3 1390.98      58 1389.12    67.7 1387.92
    77.3 1386.42      87  1384.3    96.6 1381.06   106.3 1376.87   107.71376.324
     116 1373.09   125.6 1371.16   135.3 1371.21   142.71371.874   154.6 1372.84
     261 1379.11   270.6 1379.93   280.3 1381.88     290 1385.96   299.6 1391.96
   309.3 1396.75     319 1398.39   328.6 1399.64
#Mann= 5 ,-1 , 0
       0    .016       0    5.89     .06       0   12.45     .12       0
   107.7    .045       0   142.7     .12       0
Bank Sta=116,154.6
XS Rating Curve= 0 ,0
Exp/Cntr=0.3,0.1

Type RM Length L Ch R = 1 ,1698.3  ,153.4,189.7,230
XS GIS Cut Line= 3
     1791632.686      209299.086     1791622.559      209013.279
     1791638.184      208955.119
#Sta/Elev= 30
       0 1376.43     9.5 1375.84   21.851375.986    28.6 1376.37    38.1 1377.25
    66.7 1380.69    76.3 1382.39    95.3 1386.64   104.9 1387.91   114.4 1387.34
   123.9 1384.84   133.5 1381.43     143  1378.4   152.5 1376.54   181.1 1374.14
   200.2 1373.12   219.3  1372.4   228.8 1371.73     236 1370.76   247.9 1368.68
   257.4    1369   266.9 1372.53     2711374.364   276.4 1376.78     286 1380.62
   294.6 1384.48   303.2  1388.8   320.4 1398.07     329 1402.02   346.2 1409.21
#Mann= 4 ,-1 , 0
       0     .06       0   21.85     .12       0     236    .045       0
     271     .12       0
Bank Sta=228.8,266.9
XS Rating Curve= 0 ,0
Exp/Cntr=0.3,0.1

Type RM Length L Ch R = 1 ,1508.5  ,58.9,66.6,69.1
XS GIS Cut Line= 4
     1791684.769      209342.489     1791685.059      209153.036
     1791868.219      209131.334     1791896.864      209007.202
#Sta/Elev= 30
       0 1379.08    37.9 1375.74   66.731374.401    85.2 1374.73   113.7 1377.64
   123.1 1379.07   132.6 1381.22   151.6 1386.45     161 1387.31   170.5 1386.04
   189.4 1379.94     238 1380.16   247.7 1379.47   257.4 1376.95   266.21373.276
   276.2 1369.67   286.5 1368.37   301.21369.129   315.6  1369.8   335.1 1371.21
   344.8 1373.74   383.7 1390.84   403.3 1396.68   422.9 1400.77   432.7 1401.55
   442.5 1401.55   452.3 1403.39   462.1 1407.61   491.5 1422.27   501.3 1426.25
#Mann= 4 ,-1 , 0
       0     .06       0   66.73     .12       0   266.2    .045       0
   301.2     .12       0
Bank Sta=276.2,315.6
XS Rating Curve= 0 ,0
Exp/Cntr=0.3,0.1

Type RM Length L Ch R = 1 ,1441.9  ,96.4,67.6,39.9
XS GIS Cut Line= 4
     1791717.756      209382.419     1791714.573      209190.362
     1791897.732      209168.661     1791926.378      209044.529
#Sta/Elev= 30
       0 1380.31   36.471377.363   59.181375.405    86.4 1373.64  121.271373.507
   144.1 1374.72   163.3 1376.98   172.9  1378.8   192.1 1386.16   211.5 1386.19
   221.2 1385.09   230.9 1382.73   250.3  1376.3   296.31369.319   306.3 1368.47
   318.3 1367.96   331.31368.328   337.7 1368.75   347.4 1370.08   357.1 1372.78
   376.5 1379.92   386.3 1385.16   396.1 1387.69   415.7 1390.96   454.9 1400.79
   464.7 1401.57   474.5  1400.9   484.3 1401.73   494.1 1405.36   503.9 1410.35
#Mann= 6 ,-1 , 0
       0     .06       0   36.47     .12       0   59.18     .06       0
  121.27     .12       0   296.3    .045       0   331.3     .12       0
Bank Sta=306.3,337.7
XS Rating Curve= 0 ,0
Exp/Cntr=0.3,0.1

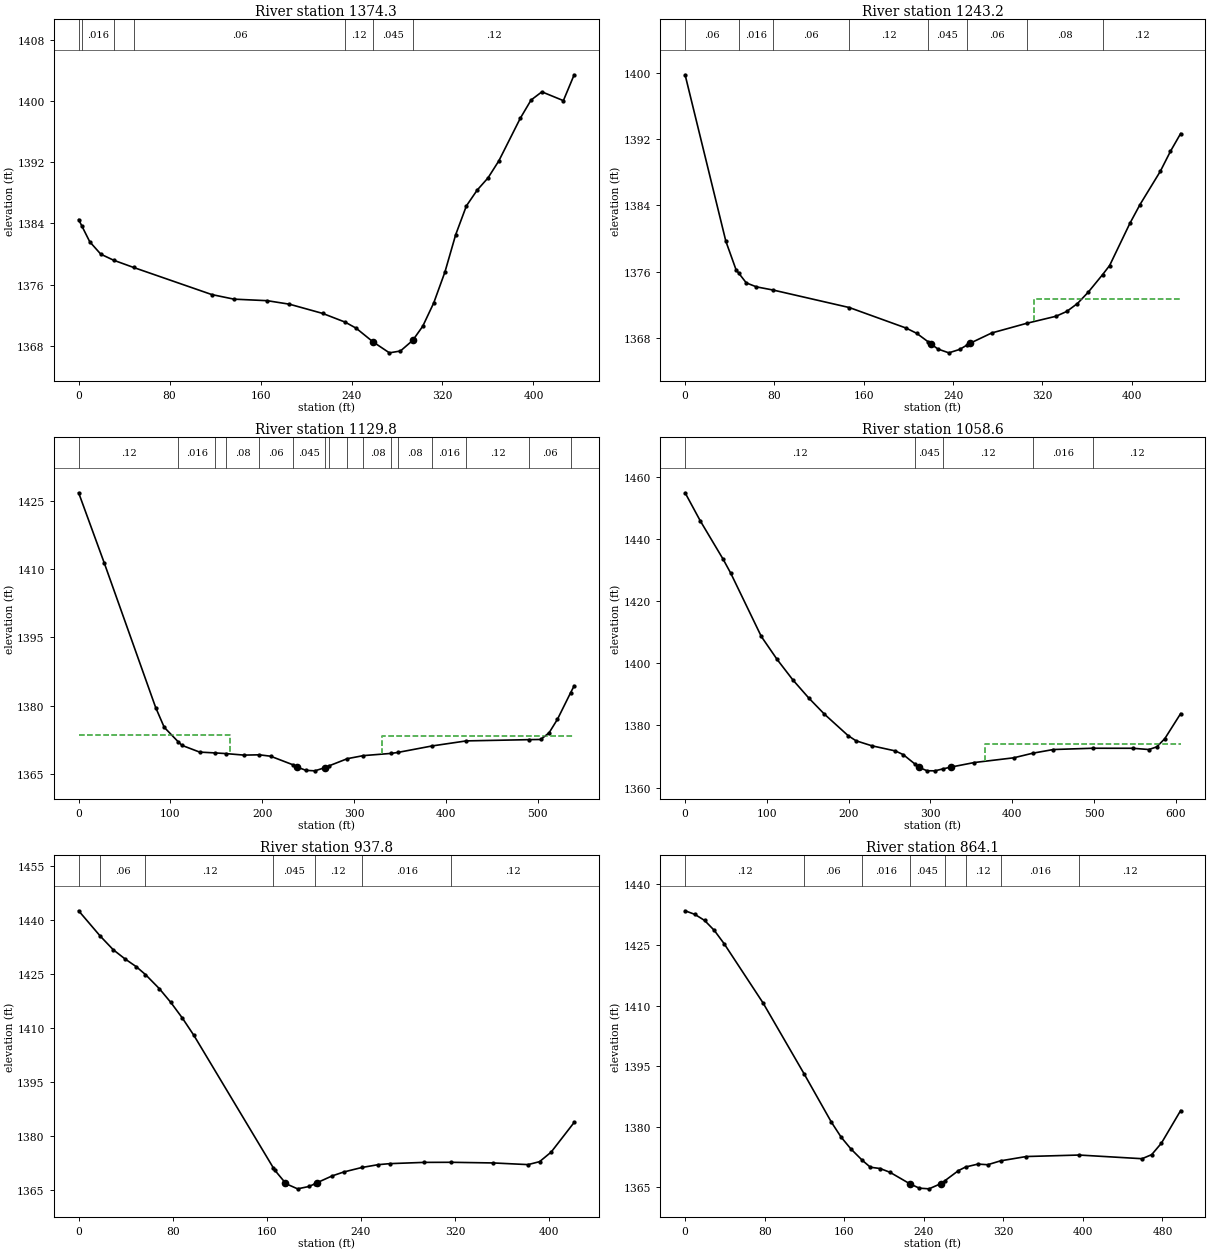
Type RM Length L Ch R = 1 ,1374.3  ,131.4,131,131
XS GIS Cut Line= 3
     1791731.644       209431.03     1791922.038      209171.265
     1791946.344      209060.154
#Sta/Elev= 30
       0  1384.5    2.671383.707     9.8 1381.59    19.5 1379.97    30.8 1379.18
   48.411378.231   117.1 1374.69   136.6 1374.09   165.9 1373.89   185.4 1373.43
   214.7 1372.22   234.41371.084     244  1370.3   258.81368.514   273.3 1367.07
     283 1367.31   293.81368.699   302.6 1370.54   312.3  1373.6   322.1 1377.62
   331.6 1382.52     341 1386.28   350.5 1388.35     360 1389.94   369.5 1392.16
   388.4 1397.74   397.9 1400.13   407.4  1401.2   426.3 1400.05   435.8 1403.43
#Mann= 7 ,-1 , 0
       0     .12       0    2.67    .016       0    30.8     .12       0
   48.41     .06       0   234.4     .12       0   258.8    .045       0
   293.8     .12       0
Bank Sta=258.8,293.8
XS Rating Curve= 0 ,0
Exp/Cntr=0.3,0.1

Type RM Length L Ch R = 1 ,1243.2  ,107.4,113.4,119.8
XS GIS Cut Line= 4
     1791908.149      209481.161     1791911.621      209408.244
     1792091.309      209159.112       1792086.1      209095.744
#Sta/Elev= 30
       0 1399.79    36.5 1379.68    45.6 1376.25   48.151375.807    54.8 1374.65
    63.9 1374.17   78.911373.784  147.13 1371.67   197.8  1369.2   207.4 1368.56
   217.51367.551  220.25 1367.26   226.6 1366.65   236.2  1366.2   245.8 1366.61
   252.5 1367.14   255.4 1367.37   274.6  1368.6  306.091369.773   332.2 1370.62
   341.8  1371.2   351.4 1372.16     361 1373.52  373.821375.634   380.2 1376.75
   398.3 1381.83   407.4 1384.11   425.6 1388.13   434.7 1390.55   443.8 1392.69
#Mann= 8 ,-1 , 0
       0     .06       0   48.15    .016       0   78.91     .06       0
  147.13     .12       0   217.5    .045       0   252.5     .06       0
  306.09     .08       0  373.82     .12       0
#XS Ineff= 2 , 0
                          312.69         1372.74
Permanent Ineff=
       F       F
Bank Sta=220.25,255.4
XS Rating Curve= 0 ,0
Exp/Cntr=0.3,0.1

Type RM Length L Ch R = 1 ,1129.8  ,70.6,71.3,72.3
XS GIS Cut Line= 4
     1791974.121      209529.772     1791979.714        209436.7
     1792234.538      209230.293     1792217.177      209113.105
#Sta/Elev= 30
       0 1426.74      28 1411.29    83.9 1379.63    93.2  1375.3  108.611372.086
   112.5 1371.34   131.8 1369.86  148.911369.677  160.071369.539     180  1369.2
  196.821369.265     209 1368.96   233.31367.083   237.9 1366.57   247.6 1365.86
   257.2 1365.75   268.31366.454  272.611366.841  292.651368.422  310.121369.089
  340.57 1369.58  347.641369.789  385.151371.219   422.21372.318  490.371372.589
   503.2 1372.63   512.3  1374.1   521.4 1377.06  535.761382.898   539.6  1384.4
#Mann= 16 ,-1 , 0
       0     .12       0  108.61    .016       0  148.91     .06       0
  160.07     .08       0  196.82     .06       0   233.3    .045       0
   268.3     .12       0  272.61     .08       0  292.65     .06       0
  310.12     .08       0  340.57     .06       0  347.64     .08       0
  385.15    .016       0   422.2     .12       0  490.37     .06       0
  535.76     .12       0
#XS Ineff= 2 , 0
          165.33  1373.6  330.65         1373.36
Permanent Ineff=
       F       F
Bank Sta=237.9,268.3
XS Rating Curve= 0 ,0
Exp/Cntr=0.3,0.1

Type RM Length L Ch R = 1 ,1058.6  ,144.3,120.8,96.8
XS GIS Cut Line= 4
     1792000.163       209593.14     1792005.756      209500.068
      1792260.58      209293.661     1792234.874      209110.614
#Sta/Elev= 30
       0 1454.99    18.6 1445.92    46.6 1433.54    55.9 1429.03    93.2 1408.68
   112.5 1401.29   131.8 1394.68   151.1 1388.89   170.4 1383.64   199.3 1376.74
     209 1375.07   228.3 1373.46   257.2 1371.79   266.8  1370.6   280.61367.679
   286.1 1366.51   295.8 1365.41   305.4 1365.38   315.6 1366.02   324.7 1366.57
   353.7 1368.06   401.9 1369.58  425.091371.061   450.4 1372.25  498.311372.661
   547.6 1372.65   567.1 1372.25   576.8  1373.1   586.6 1375.74     606 1383.82
#Mann= 5 ,-1 , 0
       0     .12       0   280.6    .045       0   315.6     .12       0
  425.09    .016       0  498.31     .12       0
#XS Ineff= 2 , 0
                          366.98         1374.02
Permanent Ineff=
       F       F
Bank Sta=286.1,324.7
XS Rating Curve= 0 ,0
Exp/Cntr=0.3,0.1

Type RM Length L Ch R = 1 ,937.8   ,112.5,73.7,31.2
XS GIS Cut Line= 2
     1792303.982      209525.432     1792240.603      209109.051
#Sta/Elev= 30
       0 1442.59   18.341435.577    29.4 1431.79    39.2 1429.29      49 1427.08
   56.831424.891    68.6 1420.99    78.4 1417.15    88.2 1412.82      98 1408.01
   165.61371.218   166.5 1370.73   175.6 1367.15   176.3 1366.87   186.1 1365.46
   195.9 1366.12   200.61366.839  202.79 1367.18   215.5 1369.05   225.3 1370.13
  240.741371.383   254.7 1372.17   264.5 1372.45   293.8  1372.8  316.781372.822
   352.6 1372.64     382 1372.18   391.8    1373   401.6 1375.64   421.2 1383.89
#Mann= 7 ,-1 , 0
       0     .12       0   18.34     .06       0   56.83     .12       0
   165.6    .045       0   200.6     .12       0  240.74    .016       0
  316.78     .12       0
Bank Sta=175.6,202.79
XS Rating Curve= 0 ,0
Exp/Cntr=0.3,0.1

Type RM Length L Ch R = 1 ,864.1   ,64.8,62.5,65.4
XS GIS Cut Line= 4
     1792405.545      209484.633     1792391.656      209298.869
       1792273.6      209298.869     1792249.457      209106.447
#Sta/Elev= 30
       0 1433.46     9.8 1432.57    19.6 1431.07    29.4 1428.59    39.2 1425.33
    78.4 1410.64  119.881393.004   147.1 1381.13   156.9 1377.42   166.7 1374.51
  178.221371.677   186.3 1369.97   196.1 1369.65     206 1368.72   226.11365.853
   235.5 1364.79   245.3 1364.62  257.46 1365.94   261.11366.608   274.8 1369.12
  282.011370.023   294.5 1370.75   304.3 1370.59  317.161371.549   343.1 1372.62
  396.211372.988   459.5 1372.08   469.2 1373.09   478.9 1375.91   498.3    1384
#Mann= 8 ,-1 , 0
       0     .12       0  119.88     .06       0  178.22    .016       0
   226.1    .045       0   261.1     .08       0  282.01     .12       0
  317.16    .016       0  396.21     .12       0
Bank Sta=226.1,257.46
XS Rating Curve= 0 ,0
Exp/Cntr=0.3,0.1

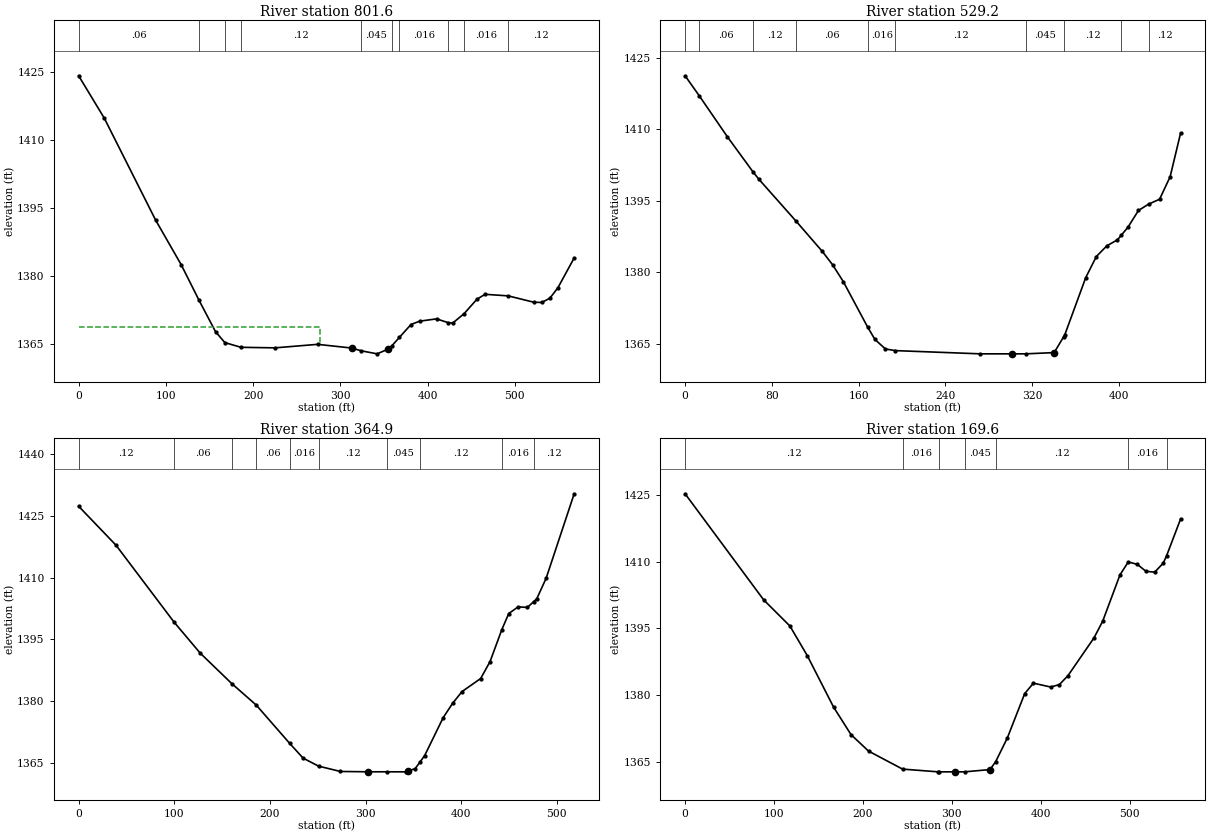
Type RM Length L Ch R = 1 ,801.6   ,227.5,272.4,315
XS GIS Cut Line= 4
     1792549.642      209442.098     1792535.753      209256.334
     1792311.795      209257.202     1792296.332      209100.197
#Sta/Elev= 30
       0 1424.15    29.4 1414.82    88.2 1392.39   117.6 1382.53  138.011374.713
   156.9  1367.8  167.591365.396  186.041364.358   225.2 1364.24   273.9 1365.01
   312.9  1364.2   323.91363.588   342.1 1362.92  354.68 1363.95   358.91364.651
  367.721366.557     381 1369.38   390.8 1370.11   410.2 1370.62  423.821369.775
   428.8  1369.7  441.851371.769   456.6 1374.96   465.9 1376.03   492.41375.683
   521.6 1374.29   530.9 1374.23   540.2 1375.18   549.4 1377.49     568 1384.04
#Mann= 10 ,-1 , 0
       0     .06       0  138.01     .12       0  167.59    .016       0
  186.04     .12       0   323.9    .045       0   358.9     .08       0
  367.72    .016       0  423.82     .08       0  441.85    .016       0
   492.4     .12       0
#XS Ineff= 2 , 0
          276.16 1368.75
Permanent Ineff=
       F       F
Bank Sta=312.9,354.68
XS Rating Curve= 0 ,0
Exp/Cntr=0.3,0.1

Type RM Length L Ch R = 1 ,529.2   ,161.4,164.3,168
XS GIS Cut Line= 2
     1792600.857      209442.098     1792618.219      208985.501
#Sta/Elev= 30
       0 1421.22   13.131416.994    38.9 1408.44   62.391401.114      68  1399.5
  102.431390.661   126.4 1384.37   136.1  1381.5   145.8 1378.02  168.411368.408
     175 1365.86   184.7 1363.85  193.951363.507   272.2 1362.83   301.4 1362.83
     314 1362.83   340.3 1363.09     349  1366.4     350 1366.78   369.4 1378.84
   379.2 1383.27   388.9 1385.52   398.6 1386.76   402.31387.771   408.3 1389.41
     418 1392.93  427.271394.254   437.5  1395.3   447.2 1400.01   456.9 1409.22
#Mann= 10 ,-1 , 0
       0     .12       0   13.13     .06       0   62.39     .12       0
  102.43     .06       0  168.41    .016       0  193.95     .12       0
     314    .045       0     349     .12       0   402.3    .016       0
  427.27     .12       0
Bank Sta=301.4,340.3
XS Rating Curve= 0 ,0
Exp/Cntr=0.3,0.1

Type RM Length L Ch R = 1 ,364.9   ,192.1,195.2,197.8
XS GIS Cut Line= 2
      1792706.76      209488.105     1792805.719      208979.425
#Sta/Elev= 30
       0 1427.35    39.1 1417.88    99.91399.168   127.1 1391.67  160.091384.276
  185.75 1379.04  220.711369.733   234.7 1366.16   250.91364.203   273.8 1362.91
   303.1 1362.83   322.1 1362.83   342.2 1362.82   344.5 1363.01     352 1363.61
   357.11365.244   361.8 1366.75   381.3 1376.02   391.1 1379.47   400.9 1382.32
   420.4 1385.49   430.2 1389.59   442.51397.342   449.8 1401.29   459.6  1402.9
   469.3 1402.77  475.781404.159   479.1 1404.87   488.9 1409.87   518.2 1430.38
#Mann= 10 ,-1 , 0
       0     .12       0    99.9     .06       0  160.09     .08       0
  185.75     .06       0  220.71    .016       0   250.9     .12       0
   322.1    .045       0   357.1     .12       0   442.5    .016       0
  475.78     .12       0
Bank Sta=303.1,344.5
XS Rating Curve= 0 ,0
Exp/Cntr=0.3,0.1

Type RM Length L Ch R = 1 ,169.6   ,161.8,169.6,177.5
XS GIS Cut Line= 4
     1792783.149      209501.994     1792928.188      209303.821
     1792976.725       209155.64     1792919.434      209010.675
#Sta/Elev= 30
       0 1425.22    88.4 1401.41   117.9 1395.55   137.5 1388.88     167 1377.36
   186.6 1371.19   206.3 1367.49  244.651363.443   284.6 1362.83  285.34 1362.83
     304 1362.83   314.4 1362.83     343 1363.34   349.41365.136   362.5 1370.45
     382 1380.39   391.8 1382.73   411.2 1381.86     421  1382.4   430.7 1384.42
     460 1392.91   469.7 1396.62   489.2 1407.04   498.51409.926   508.7 1409.38
   518.4 1407.82   528.2 1407.64   537.9 1409.66  541.681411.363   557.4 1419.59
#Mann= 7 ,-1 , 0
       0     .12       0  244.65    .016       0  285.34     .12       0
   314.4    .045       0   349.4     .12       0   498.5    .016       0
  541.68     .12       0
Bank Sta=304,343
XS Rating Curve= 0 ,0
Exp/Cntr=0.3,0.1

Chan Stop Cuts=-1
Use User Specified Reach Order=0
Composite Channel Slope=5